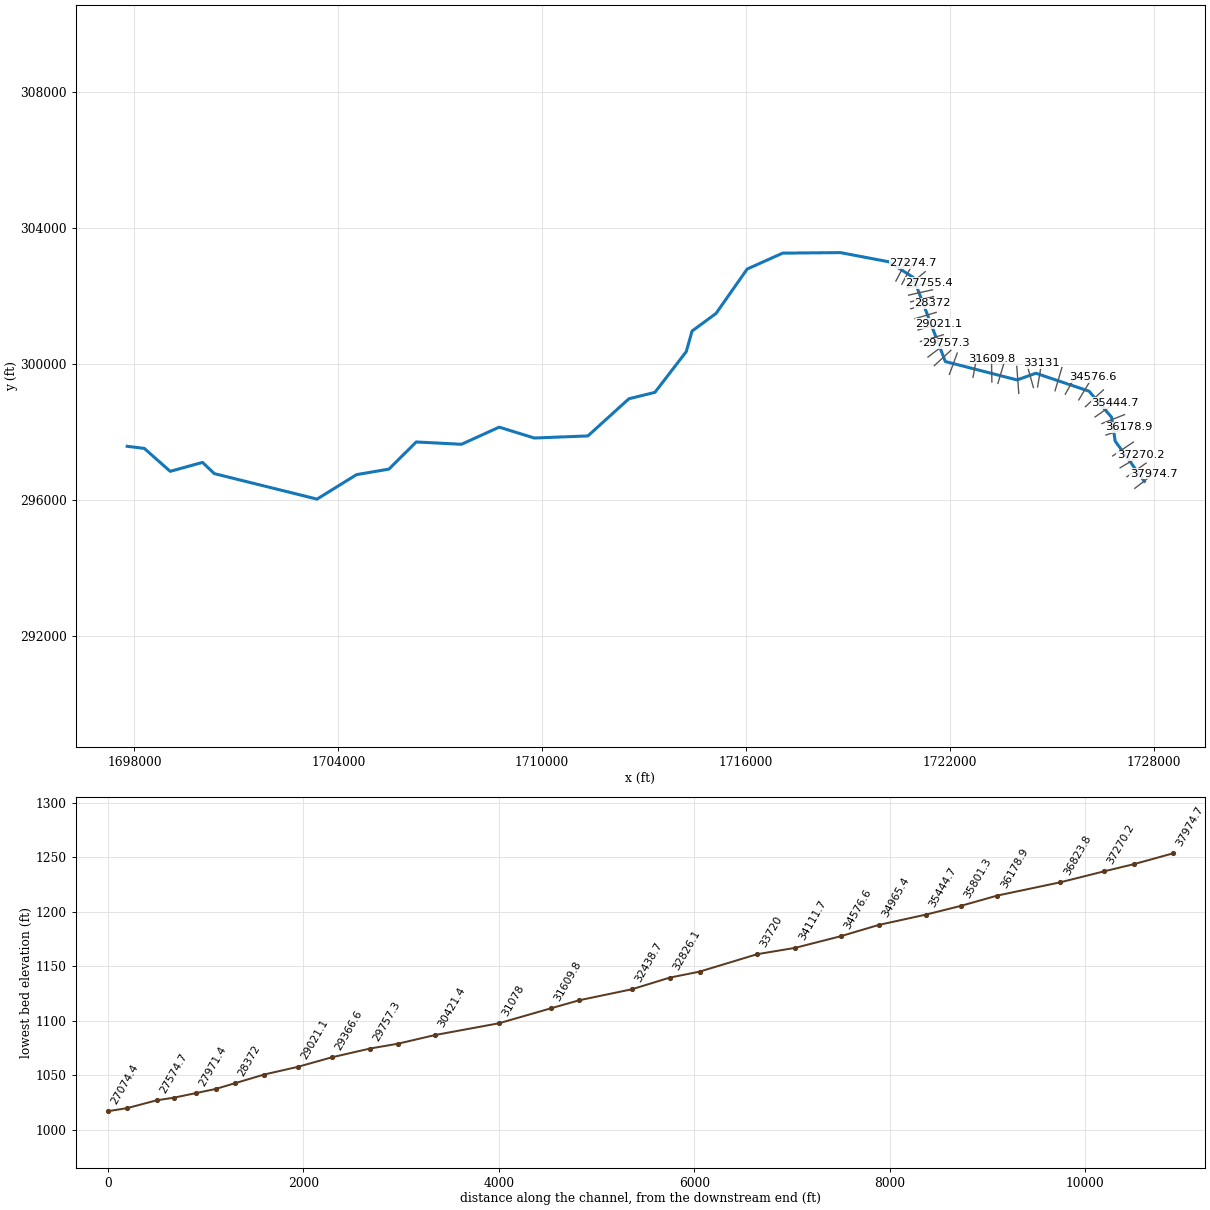
--- RUMCRK.prj (project) ---

Proj Title=RUMCRK
Current Plan=p01
Default Exp/Contr=0,0
English Units
Geom File=g01
Flow File=f01
Plan File=p01
BEGIN DESCRIPTION:
END DESCRIPTION:
DSS Export Rating Curves= 0
DSS Export Rating Curve Sorted= 0
DSS Export Volume Flow Curves= 0
DXF OffsetX= 0
DXF OffsetY= 0
DXF ScaleX= 0
DXF ScaleY= 0

--- RUMCRK.p01 (plan) ---

Plan Title=Floodplain
Program Version=4.00
Geom File=g01
Flow File=f01
K Sum by GR=0
Std Step Tol=0.01
Critical Tol=0.01
Num of Std Step Trials=20
Max Error Tol=0.3
Flow Tol Ratio=0.001
Split Flow NTrial=30
Split Flow Tol=0.02
Split Flow Ratio=0.02
Log Output Level=0
Friction Slope Method=1
Unsteady Friction Slope Method=2
Unsteady Bridges Friction Slope Method=1
Global Log Level=0
CheckData=False
Run HTab=0
Run UNet=0
Run PostProcess=0
UNET Theta=0
UNET Theta Warmup=0
UNET ZTol=0
UNET ZSATol=0
UNET MxIter=0
UNET MaxInSteps=0
UNET DtIC=0
UNET DtMin=0
UNET MaxCRTS=0
UNET WFStab=0
UNET SFStab=0
UNET WFX=0
UNET SFX=0
UNET DSS MLevel=0
UNET DZMax Abort=0
UNET Convert EG Bridges=0
UNET Use Existing IB Tables=0
UNET Froude Limit=0
UNET Froude Power=0
Write IC File=0
Echo Input=False
Echo Output=False
Write Detailed=0

--- RUMCRK.f01 (steady flow) ---

Flow Title=NFF Regression Equation
Program Version=4.10
Number of Profiles= 1
Profile Names=P100yr
River Rch & RM=RUMCRK,Main            ,37974.7
1004.888
River Rch & RM=RUMCRK,Main            ,35444.7
1079.751
River Rch & RM=RUMCRK,Main            ,33131
1167.979
River Rch & RM=RUMCRK,Main            ,31899.8
1273.303
River Rch & RM=RUMCRK,Main            ,27574.7
1410.717
River Rch & RM=RUMCRK,Main            ,27274.7
1625.726
River Rch & RM=RUMCRK,Main            ,24759.1
1727.079
River Rch & RM=RUMCRK,Main            ,18869.5
1898.923
River Rch & RM=RUMCRK,Main            ,14401.9
2109.131
River Rch & RM=RUMCRK,Main            ,14168.5
2798.688
River Rch & RM=RUMCRK,Main            ,7953.8
3037.982
River Rch & RM=RUMCRK,Main            ,7619
 3807.47
River Rch & RM=RUMCRK,Main            ,774.7
3965.906
Boundary for River Rch & Prof#=RUMCRK,Main            , 1
Up Type= 0
Dn Type= 3
Dn Slope=0.010731
DSS Import GetInterval= 0
DSS Import GetPeak= 0
DSS Import FillOption= 0

--- RUMCRK.g01 (geometry) ---

Geom Title=USGS 10m DEM
Program Version=4.10

River Reach=RUMCRK          ,Main
Reach XY= 30
     1727725.501       296548.45     1726866.115      297729.817
      1726759.56      298434.005      1726095.91      299200.735
     1724531.177      299727.718     1723978.715      299530.823
     1721866.152      300071.704     1720918.742      302547.942
     1720207.605      303004.274     1718778.383      303275.294
     1717079.298      303260.237     1716034.599      302792.323
     1715118.461      301487.028     1714411.957      300968.153
     1714241.701      300363.571     1713319.771      299165.989
     1712551.883      298976.044     1711346.193      297883.858
     1709769.879      297822.474     1708735.603      298142.138
     1707624.886      297638.319     1706294.111      297706.653
     1705490.318      296908.651     1704535.959      296745.345
     1703374.281      296026.101     1700350.213      296775.458
      1700003.91      297105.546     1699053.025      296842.634
     1698289.193      297517.885     1697787.691      297578.112

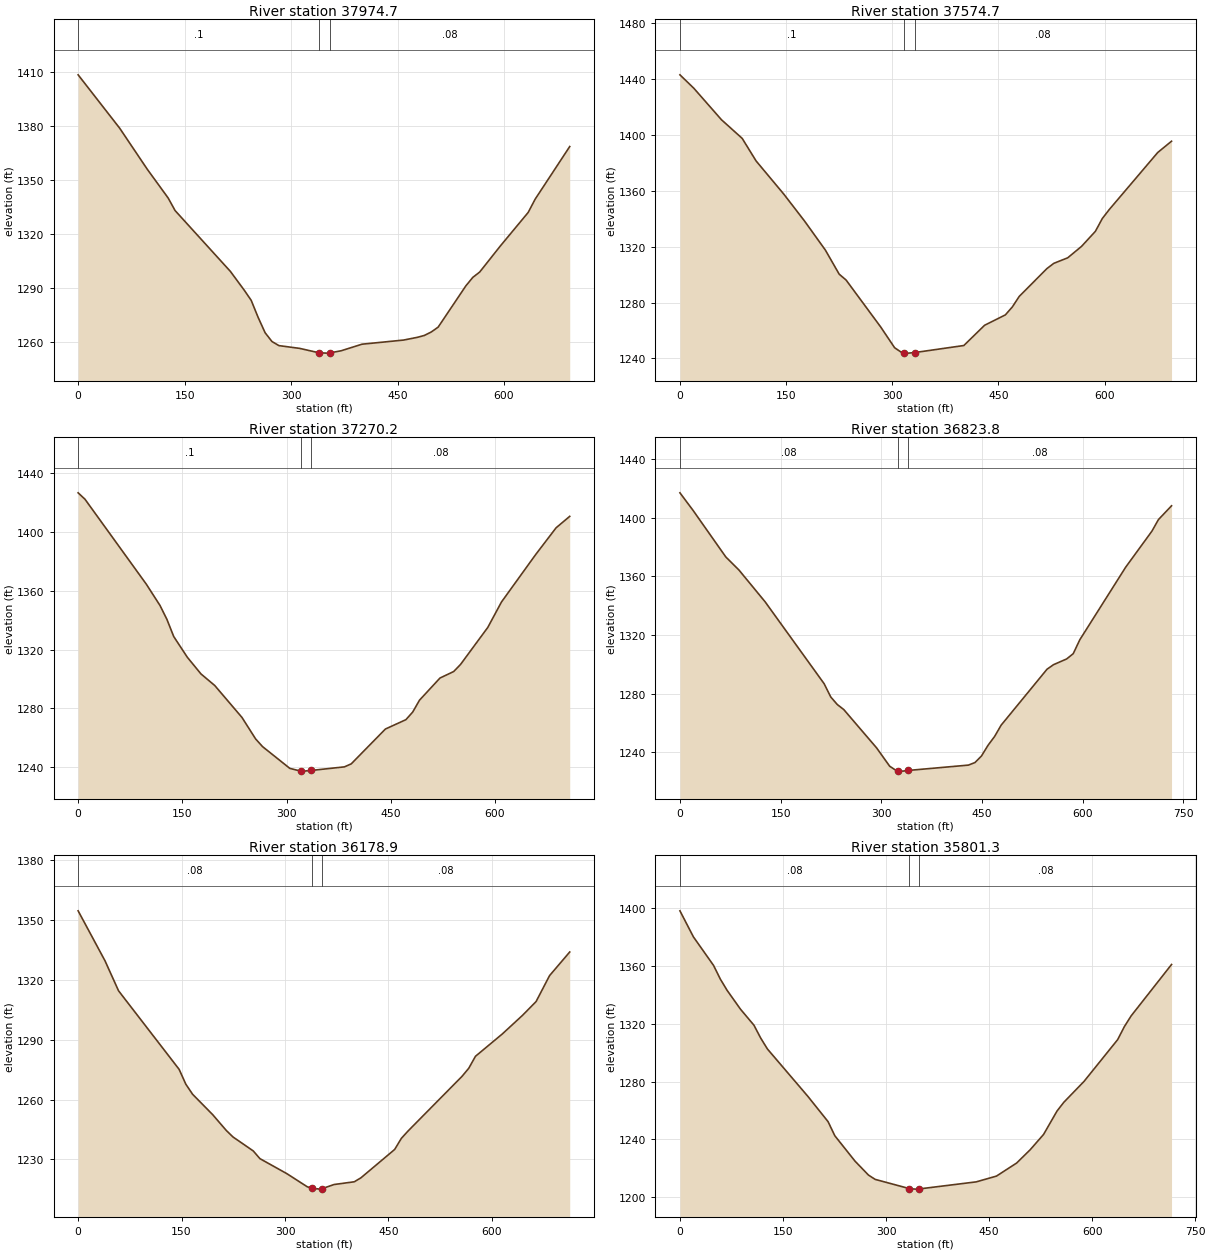
Type RM Length L Ch R = 1 ,37974.7 ,400.8,399.9,398.9
XS GIS Cut Line= 2
     1727445.439      296343.734     1727992.527      296768.325
#Sta/Elev= 30
       0 1408.68    58.5    1379    97.5 1356.07   126.8 1340.13   136.6 1333.11
   214.6  1299.2   234.1 1288.74   243.8 1283.14   253.6 1273.63   263.4 1265.11
   273.1  1260.2   282.9 1257.93   312.1 1256.39   339.8  1253.9   351.1 1253.75
   354.8 1253.89   370.6 1255.07   399.9 1258.72   458.4 1261.02   477.9 1262.54
   487.7 1263.59   497.4  1265.5   507.2 1268.24   546.2  1291.2     556 1295.92
   565.7  1298.9     595 1313.51     634 1332.07   643.8 1339.46   692.5 1368.75
#Mann= 3 , 0 , 0
       0      .1       0   339.8    .045       0   354.8     .08       0
Bank Sta=339.8,354.8
XS Rating Curve= 0 ,0
Exp/Cntr=0.3,0.1

Type RM Length L Ch R = 1 ,37574.7 ,306.2,304.4,302.6
XS GIS Cut Line= 2
     1727210.953      296684.039     1727777.484      297086.008
#Sta/Elev= 30
       0 1442.91    19.6 1433.32    58.7 1410.77      88 1397.42   107.6 1381.31
   146.8 1357.54   176.1  1338.3   205.5 1317.54     225 1300.33   234.8  1296.1
   283.7 1262.52   303.3 1247.72   313.1 1244.35     317 1244.15   322.9 1243.84
     332 1244.27   401.1 1249.28   430.5 1263.78   459.8 1271.19   469.6 1276.84
   479.4 1284.41   518.5 1304.31   528.3 1308.08   547.9 1312.02   567.5 1320.23
     587 1330.96   596.8 1340.14   606.6 1346.54   675.1 1387.36   694.6 1395.42
#Mann= 3 , 0 , 0
       0      .1       0     317    .045       0     332     .08       0
Bank Sta=317,332
XS Rating Curve= 0 ,0
Exp/Cntr=0.3,0.1

Type RM Length L Ch R = 1 ,37270.2 ,445.8,446.4,447
XS GIS Cut Line= 2
     1727011.879      296946.147     1727619.073      297309.559
#Sta/Elev= 30
       0 1426.62     9.8 1422.31    98.3 1364.37   117.9 1349.95   127.8 1340.54
   137.6 1328.86   157.2 1314.74   176.9 1303.37   196.6 1295.56   235.9 1273.76
   255.5 1259.17   265.4 1253.98   304.7 1239.15   320.1 1237.31   324.3 1237.27
   335.1  1237.7   383.3 1240.17   393.1  1242.2   442.3 1265.91   471.8 1272.28
   481.6 1277.46   491.4 1285.56   520.9 1300.62   540.6 1305.03   550.4 1309.83
   589.7 1335.06   609.4 1352.36   658.5 1384.56     688 1402.83   707.6 1410.61
#Mann= 3 , 0 , 0
       0      .1       0   320.1    .045       0   335.1     .08       0
Bank Sta=320.1,335.1
XS Rating Curve= 0 ,0
Exp/Cntr=0.3,0.1

Type RM Length L Ch R = 1 ,36823.8 ,649.8,644,638.2
XS GIS Cut Line= 2
     1726791.414      297294.706     1727399.916      297702.036
#Sta/Elev= 30
       0 1416.94    19.5    1405    68.3 1373.24    87.9 1364.32   126.9 1342.63
   214.8  1286.8   224.6 1277.81   234.3 1272.66   244.1 1269.17   292.9 1243.09
   312.4 1230.58   322.2 1227.63   324.5 1227.54     332 1227.24   339.5 1227.68
   429.6 1231.34   439.4 1233.08   449.1 1237.55   458.9 1244.86   468.6 1250.82
   478.4 1258.56   546.8 1296.73   556.5 1299.82     576 1303.71   585.8 1307.32
   595.6  1316.8   663.9 1366.26     703 1390.82   712.7 1398.71   732.2  1408.1
#Mann= 3 , 0 , 0
       0     .08       0   324.5    .045       0   339.5     .08       0
Bank Sta=324.5,339.5
XS Rating Curve= 0 ,0
Exp/Cntr=0.3,0.1

Type RM Length L Ch R = 1 ,36178.9 ,376.5,377.5,378.6
XS GIS Cut Line= 2
     1726594.245      297909.807     1727269.405      298138.507
#Sta/Elev= 30
       0 1354.62    39.1 1329.48    58.6 1314.53   146.5 1275.11   156.2 1267.67
     166 1262.63   195.3 1252.34   214.8 1244.49   224.6 1241.21   253.9 1234.22
   263.6 1230.35   302.7 1222.81     332 1216.29   338.9 1215.47   351.5 1215.06
   353.9 1215.32   371.1 1217.37   400.4 1218.74   410.1 1220.74     459 1234.96
   468.7 1240.53   478.5 1244.24   556.6  1271.6   566.4 1275.66   576.1 1281.66
   615.2 1292.91   644.5 1302.26     664 1309.11   683.6 1322.14   712.8 1333.97
#Mann= 3 , 0 , 0
       0     .08       0   338.9    .045       0   353.9     .08       0
Bank Sta=338.9,353.9
XS Rating Curve= 0 ,0
Exp/Cntr=0.3,0.1

Type RM Length L Ch R = 1 ,35801.3 ,351,356.3,361.6
XS GIS Cut Line= 2
      1726474.05      298248.136      1727140.11      298510.019
#Sta/Elev= 30
       0 1398.19    19.6 1380.17      49 1360.35    58.8 1350.92    68.6 1343.18
    88.2 1330.05   107.8 1318.96   117.6 1310.05   127.4 1302.51   186.3  1269.7
   215.7 1252.19   225.5 1242.44   254.9 1224.87   274.5 1215.21   284.3 1212.22
   333.6 1205.91   343.1 1205.49   348.6 1205.64   431.4 1210.52   460.8 1214.51
   490.2 1223.56   509.8  1232.7   529.4 1243.36     549 1259.58   558.8 1265.58
   588.2 1280.03   637.3 1309.03   647.1 1318.08   656.9 1325.46   715.7 1361.04
#Mann= 3 , 0 , 0
       0     .08       0   333.6    .045       0   348.6     .08       0
Bank Sta=333.6,348.6
XS Rating Curve= 0 ,0
Exp/Cntr=0.3,0.1

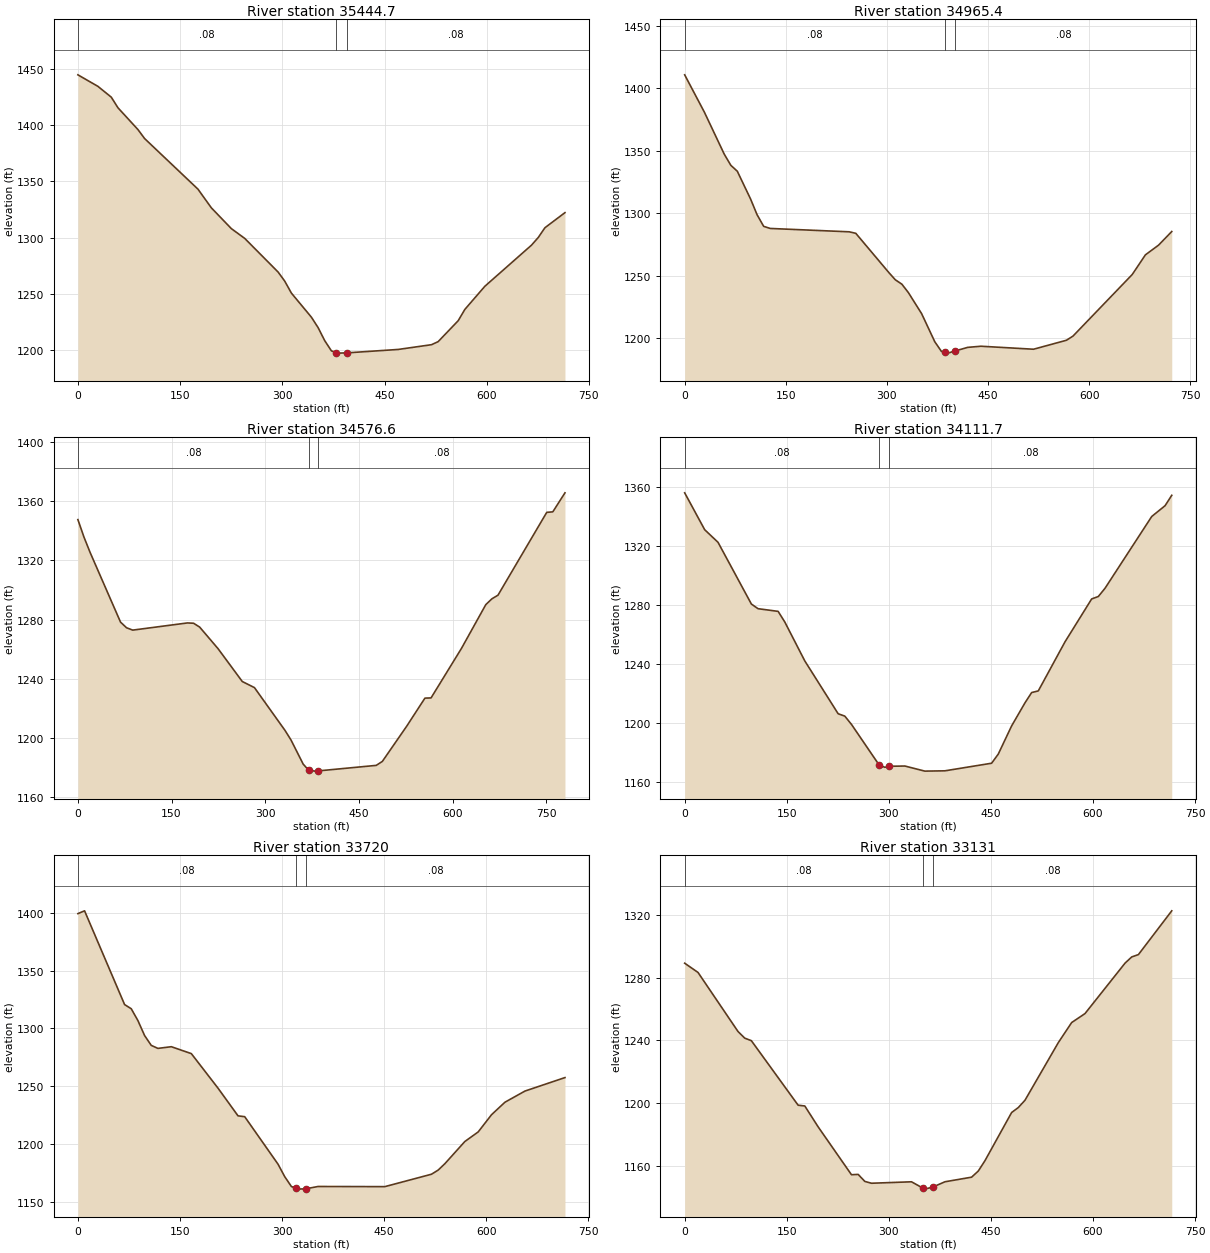
Type RM Length L Ch R = 1 ,35444.7 ,476.4,479.5,482.5
XS GIS Cut Line= 2
      1726272.51      298440.818     1726858.271      298850.446
#Sta/Elev= 30
       0  1444.4    29.4 1434.17      49 1424.58    58.8 1415.16    88.1 1395.87
    97.9 1387.87   176.2 1342.99   195.8 1326.44   225.2 1307.96   244.8 1299.31
   293.8 1269.45   303.5 1261.44   313.3 1250.79   342.7 1229.38   352.5 1220.17
   362.3  1208.5   372.1 1199.49   379.5 1197.99   381.9 1197.51   394.5 1197.73
     470 1200.77     519 1204.99   528.7  1207.7   558.1 1226.27   567.9 1236.31
   597.3 1256.86   665.8 1293.36   675.6 1300.09   685.4 1308.75   714.8 1322.14
#Mann= 3 , 0 , 0
       0     .08       0   379.5    .045       0   394.5     .08       0
Bank Sta=379.5,394.5
XS Rating Curve= 0 ,0
Exp/Cntr=0.3,0.1

Type RM Length L Ch R = 1 ,34965.4 ,382.4,388.6,394.8
XS GIS Cut Line= 2
     1725990.734      298744.209     1726518.384      299237.993
#Sta/Elev= 30
       0 1410.78    29.3 1380.82    58.6 1347.42    68.4 1338.43    78.1 1333.62
    97.7 1311.49   107.4 1298.88   117.2 1289.54     127 1287.85   244.1 1285.16
   253.9 1283.96   302.7 1252.71   312.5 1246.79   322.3 1243.24     332 1236.47
   351.6 1219.64   371.1  1197.2   380.9  1189.5   386.4  1188.7   390.6 1188.09
   401.4 1189.84   419.9 1192.69   439.5 1193.61   517.6 1191.21   566.4 1198.38
   576.2 1201.74   664.1 1251.03   683.6 1266.73   703.1 1274.48   722.7  1285.4
#Mann= 3 , 0 , 0
       0     .08       0   386.4    .045       0   401.4     .08       0
Bank Sta=386.4,401.4
XS Rating Curve= 0 ,0
Exp/Cntr=0.3,0.1

Type RM Length L Ch R = 1 ,34576.6 ,464.1,464.8,465.4
XS GIS Cut Line= 2
     1725793.326      298943.286     1726196.347      299611.228
#Sta/Elev= 30
       0 1347.61     9.8 1335.73    19.5  1325.5    68.3 1278.37      78 1274.56
    87.8 1272.98   175.5 1277.83   185.3 1277.62     195 1275.03   224.3 1260.55
   263.3 1238.26   282.8 1234.14   331.6 1205.32   341.3  1198.8   360.8  1182.5
   369.9 1178.24   380.3 1177.75   384.9  1177.9   477.8 1181.63   487.6  1184.3
   526.6 1208.08   555.8 1227.05   565.6 1227.19   614.3 1260.61   653.3 1290.19
   663.1 1294.13   672.8 1296.57   750.9 1352.51   760.6 1352.85   780.1  1365.7
#Mann= 3 , 0 , 0
       0     .08       0   369.9    .045       0   384.9     .08       0
Bank Sta=369.9,384.9
XS Rating Curve= 0 ,0
Exp/Cntr=0.3,0.1

Type RM Length L Ch R = 1 ,34111.7 ,386.4,391.4,396.5
XS GIS Cut Line= 2
     1725398.038      299113.405     1725749.882      299736.641
#Sta/Elev= 30
       0 1355.87    29.4 1330.85      49  1322.3      98 1280.44   107.8 1277.28
   137.3 1275.46   147.1 1268.27   176.5 1241.85   225.5 1206.03   235.3  1204.4
   245.1 1198.79   285.7 1171.29   294.1  1169.7   300.7 1170.39   323.5 1170.56
   352.9  1167.1   382.4 1167.31     451 1172.46   460.8 1178.67   480.4 1197.76
     500  1213.4   509.8 1220.38   519.6 1221.52   558.8 1254.77     598 1283.88
   607.8 1285.55   617.6  1291.1   686.3 1339.83   705.9 1347.15   715.7 1354.19
#Mann= 3 , 0 , 0
       0     .08       0   285.7    .045       0   300.7     .08       0
Bank Sta=285.7,300.7
XS Rating Curve= 0 ,0
Exp/Cntr=0.3,0.1

Type RM Length L Ch R = 1 ,33720   ,585.5,588.5,591.5
XS GIS Cut Line= 2
     1725096.301       299212.78     1725299.115      299899.136
#Sta/Elev= 30
       0 1399.24     9.8 1401.66    68.6 1320.68    78.4 1317.04    88.2 1306.83
      98 1293.91   107.8  1285.4   117.6  1282.8   137.3 1284.25   166.7 1278.28
   205.9 1248.44   235.3 1224.51   245.1  1223.8   294.1 1182.74   303.9 1171.99
   313.7 1163.47   320.3 1161.94   323.5  1161.2   335.3 1161.53   352.9 1163.48
     451 1163.35   519.6 1174.08   529.4 1177.66   539.2 1183.16   568.6 1202.35
   588.2 1210.63   607.8 1225.49   627.5 1236.29   656.9 1245.93   715.7 1257.58
#Mann= 3 , 0 , 0
       0     .08       0   320.3    .045       0   335.3     .08       0
Bank Sta=320.3,335.3
XS Rating Curve= 0 ,0
Exp/Cntr=0.3,0.1

Type RM Length L Ch R = 1 ,33131   ,294.9,305,315.2
XS GIS Cut Line= 2
     1724581.649       299324.81     1724700.728      300030.528
#Sta/Elev= 30
       0 1289.22    19.6 1283.32    78.4 1245.66    88.2 1241.47      98 1239.83
   166.7 1198.71   176.5 1198.22   196.1 1184.92   245.1 1154.39   254.9 1154.61
   264.7 1150.13   274.5 1148.97   333.3 1149.89   350.3  1145.8   352.9 1145.22
   365.3 1146.67   382.4  1149.9   421.6 1152.84   431.4 1156.74   441.2 1163.32
   480.4 1194.04   490.2 1197.21     500 1201.84     549 1238.59   568.6 1251.38
   588.2  1257.1   647.1 1289.28   656.9 1293.22   666.7  1294.7   715.7  1322.6
#Mann= 3 , 0 , 0
       0     .08       0   350.3    .045       0   365.3     .08       0
Bank Sta=350.3,365.3
XS Rating Curve= 0 ,0
Exp/Cntr=0.3,0.1

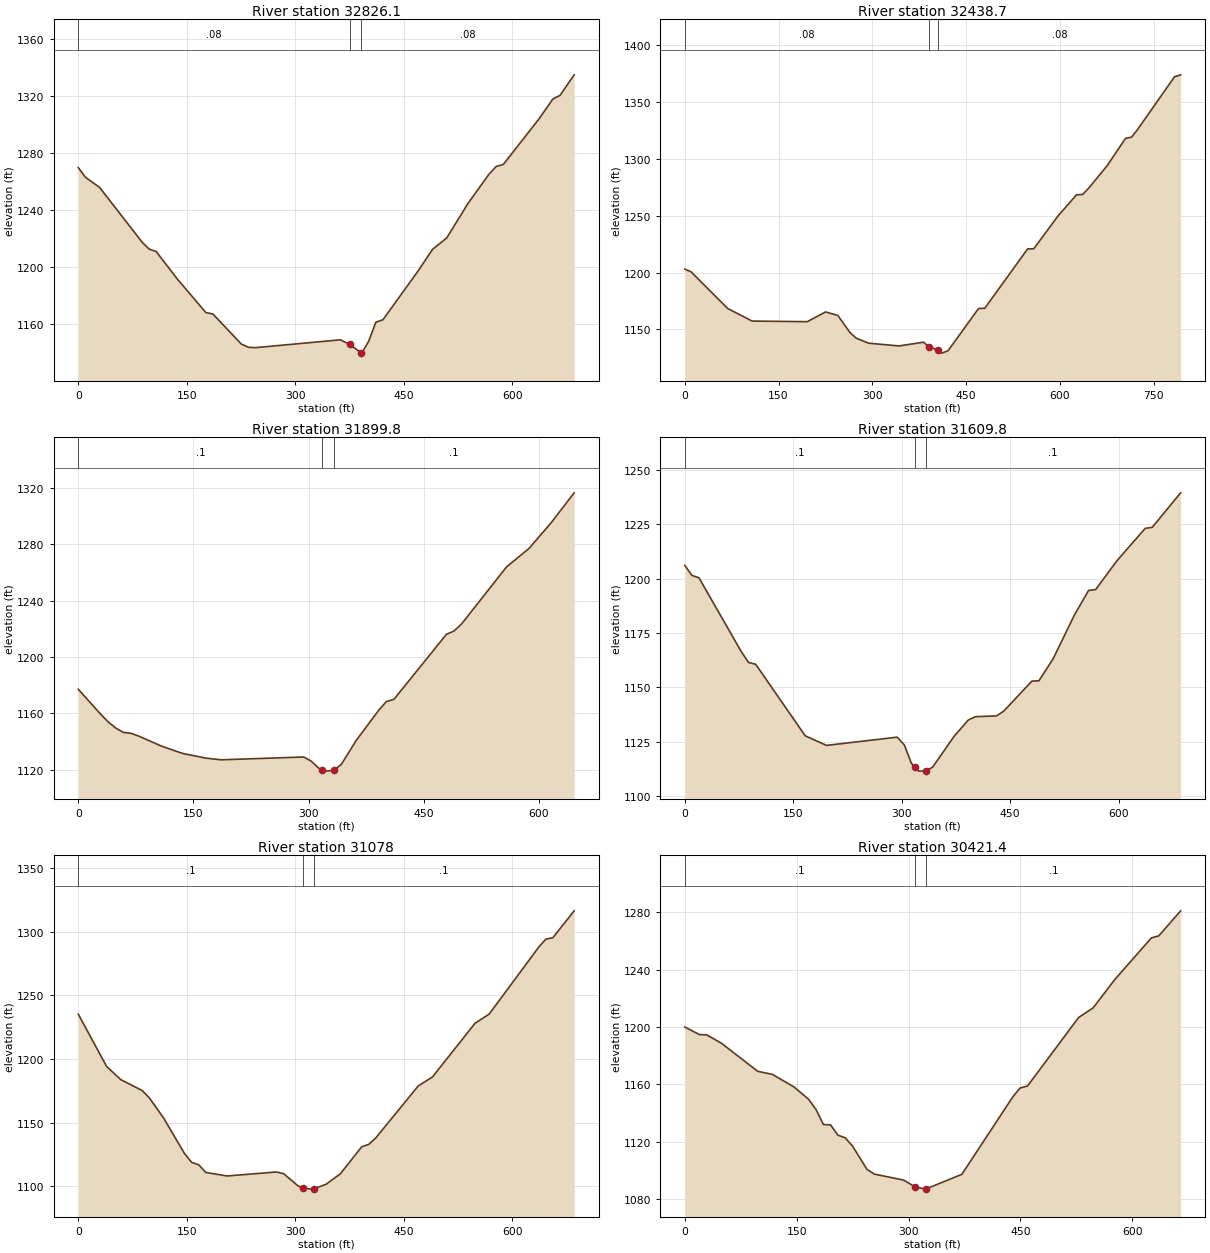
Type RM Length L Ch R = 1 ,32826.1 ,391.7,387.2,382.7
XS GIS Cut Line= 2
     1724459.193      299306.826     1724274.338      299967.052
#Sta/Elev= 30
       0 1269.74     9.8 1262.95    29.4 1255.87    88.2 1217.45      98 1212.58
   107.7 1210.91   137.1 1191.51   176.3 1168.18   186.1 1167.16   225.3  1146.1
   235.1 1143.82   244.9 1143.56   362.4 1149.05   375.4 1145.81   390.4 1140.11
   391.8 1139.72   401.6 1148.14   411.4 1161.39   421.2  1163.1   470.1 1197.49
   489.7 1212.43   509.3 1220.39   538.7 1244.55   568.1  1265.3   577.9 1270.56
   587.7 1271.97   636.6 1303.61   656.2 1317.83     666 1320.31   685.6 1334.76
#Mann= 3 , 0 , 0
       0     .08       0   375.4    .045       0   390.4     .08       0
Bank Sta=375.4,390.4
XS Rating Curve= 0 ,0
Exp/Cntr=0.3,0.1

Type RM Length L Ch R = 1 ,32438.7 ,547,538.8,530.5
XS GIS Cut Line= 2
     1724028.238      299137.022      1723969.55      299928.185
#Sta/Elev= 30
       0    1203     9.8 1200.74    68.6 1168.36   107.7 1157.26   195.9 1156.72
   225.3  1165.3   244.9 1162.17   264.4 1147.12   274.2 1142.24   293.8 1137.82
   342.8 1135.37     382 1138.69   390.3 1134.63   405.3 1131.72   411.4 1129.04
   421.2 1131.16   470.1 1168.39   479.9 1168.48   548.5  1220.8   558.3 1220.88
   597.4 1250.01   626.8 1268.42   636.6  1268.7   646.4 1274.38   675.8 1294.11
   705.2 1318.13     715 1319.25   724.8 1326.21   783.5 1372.34   793.3 1374.06
#Mann= 3 , 0 , 0
       0     .08       0   390.3    .045       0   405.3     .08       0
Bank Sta=390.3,405.3
XS Rating Curve= 0 ,0
Exp/Cntr=0.3,0.1

Type RM Length L Ch R = 1 ,31899.8 ,283,289.9,296.8
XS GIS Cut Line= 2
     1723414.518      299429.185     1723599.168      300047.999
#Sta/Elev= 30
       0 1177.06    29.4 1159.22    39.1 1153.82    48.9 1149.48    58.7 1146.46
    68.5 1145.82    78.3 1143.92   107.6 1136.89   127.2 1133.12     137 1131.37
   166.3 1128.18   185.9 1126.98   293.5 1129.01   303.3 1126.07   313.1 1121.04
   317.7 1120.06   322.9 1118.95   332.7 1119.52   342.5 1123.68     362 1140.78
   391.4 1162.27   401.2 1168.37     411  1169.9   479.4  1216.1   489.2 1218.45
     499 1223.36   557.7 1263.98   587.1 1277.15   616.4 1295.75   645.8 1316.62
#Mann= 3 , 0 , 0
       0      .1       0   317.7    .045       0   332.7      .1       0
Bank Sta=317.7,332.7
XS Rating Curve= 0 ,0
Exp/Cntr=0.3,0.1

Type RM Length L Ch R = 1 ,31609.8 ,535.7,531.4,527
XS GIS Cut Line= 2
     1723236.788      299469.788     1723225.017      300155.304
#Sta/Elev= 30
       0 1206.13     9.8 1201.54    19.6 1200.41    78.4 1166.32    88.2 1161.48
      98 1160.69   166.5 1127.79   195.9 1123.38   293.8 1127.17   303.6 1123.54
   313.4 1115.12   318.3 1113.34   323.2 1111.55   333.3 1111.66   342.8 1113.39
   372.2 1127.48   391.8 1134.98   401.6 1136.57     431 1136.94   440.8 1139.05
   479.9 1152.92   489.7 1153.09   509.3 1163.18   538.7 1183.29   558.3 1194.58
   568.1    1195   597.5 1208.24   636.6 1223.13   646.4 1223.64   685.6 1239.48
#Mann= 3 , 0 , 0
       0      .1       0   318.3    .045       0   333.3      .1       0
Bank Sta=318.3,333.3
XS Rating Curve= 0 ,0
Exp/Cntr=0.3,0.1

Type RM Length L Ch R = 1 ,31078   ,660.5,656.5,652.6
XS GIS Cut Line= 2
     1722681.882      299611.541     1722807.536      300285.545
#Sta/Elev= 30
       0 1235.26    39.2 1194.14    58.8 1183.84    88.2 1175.32      98 1169.68
   117.5 1154.05   146.9 1125.75   156.7 1118.86   166.5 1116.89   176.3 1110.91
   205.7 1108.14   274.2  1111.3     284 1109.92   303.6 1100.46   310.5 1098.69
   323.2 1097.81   325.5 1097.99   342.8 1101.71   362.4  1109.9   391.8 1131.06
   401.6 1133.01   411.4 1138.12   470.1 1178.96   489.7 1185.96   548.5 1228.14
   568.1 1235.39   636.6 1287.96   646.4 1294.25   656.2 1295.41   685.6 1316.52
#Mann= 3 , 0 , 0
       0      .1       0   310.5    .045       0   325.5      .1       0
Bank Sta=310.5,325.5
XS Rating Curve= 0 ,0
Exp/Cntr=0.3,0.1

Type RM Length L Ch R = 1 ,30421.4 ,386.3,375.6,365
XS GIS Cut Line= 2
     1721987.108      299697.142     1722217.177      300320.888
#Sta/Elev= 30
       0 1199.93    19.6 1194.68    29.3 1194.48    48.9 1188.73    97.8 1169.05
   117.3 1166.97   146.6 1158.12   166.2 1149.47     176 1142.42   185.8 1132.02
   195.5 1131.68   205.3 1124.59   215.1 1122.72   224.9 1116.96   244.4 1100.65
   254.2 1097.42   293.3 1093.28   308.6 1088.57   322.6 1086.96   323.6 1087.13
   371.5 1097.29     440 1151.43   449.7 1157.48   459.5 1158.81     528 1206.56
   547.5 1213.28   576.8 1233.19   625.7  1262.1   635.5 1263.46   664.8 1280.92
#Mann= 3 , 0 , 0
       0      .1       0   308.6    .045       0   323.6      .1       0
Bank Sta=308.6,323.6
XS Rating Curve= 0 ,0
Exp/Cntr=0.3,0.1

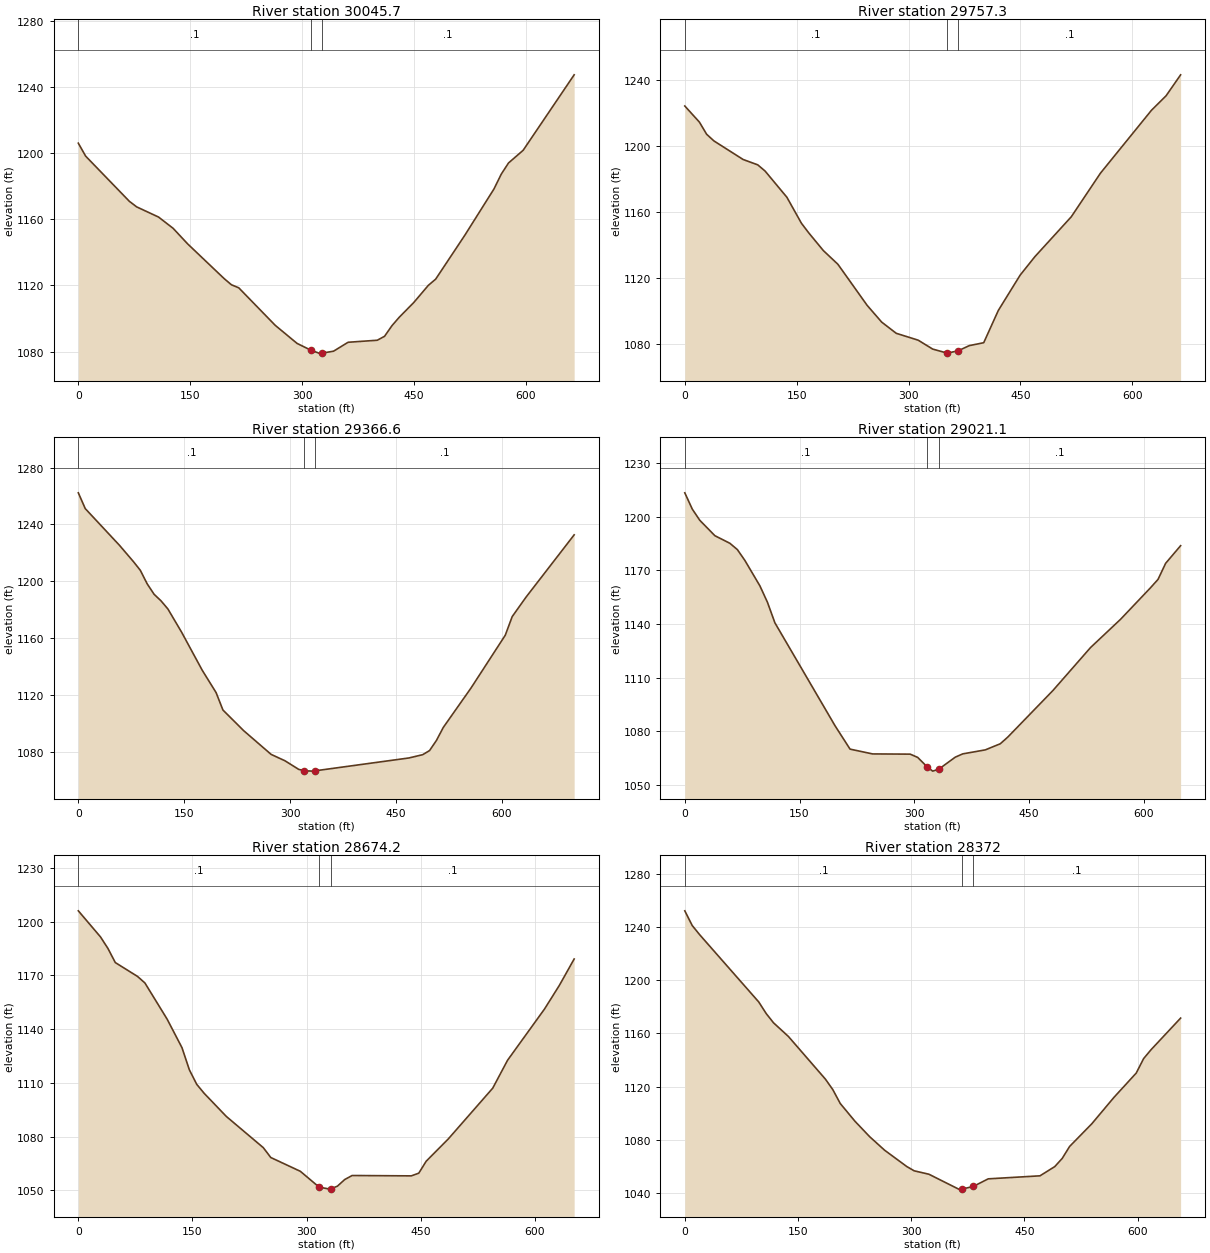
Type RM Length L Ch R = 1 ,30045.7 ,290.5,288.2,285.9
XS GIS Cut Line= 2
     1721541.821       299950.66     1722030.399      300401.529
#Sta/Elev= 30
       0 1205.94     9.8 1198.13    68.4 1170.83    78.2 1167.46   107.6 1161.29
   127.1 1154.49   146.6 1145.08   195.5 1124.11   205.3 1120.37   215.1 1118.54
     264 1095.87   293.3 1084.94   311.9 1080.81   322.6 1079.07   326.9 1079.08
   342.2 1080.24   361.7 1085.63   400.8 1086.86   410.6 1089.25   420.4 1095.59
   430.2 1100.71   449.7 1109.63   469.3 1120.04   479.1 1123.77   518.2  1150.3
   557.3 1178.29   567.1 1187.27   576.8 1193.99   596.4 1201.65   664.8 1247.26
#Mann= 3 , 0 , 0
       0      .1       0   311.9    .045       0   326.9      .1       0
Bank Sta=311.9,326.9
XS Rating Curve= 0 ,0
Exp/Cntr=0.3,0.1

Type RM Length L Ch R = 1 ,29757.3 ,398.7,390.6,382.5
XS GIS Cut Line= 2
     1721355.408      300203.827     1721885.859      300604.592
#Sta/Elev= 30
       0 1224.52    19.6 1214.74    29.3 1207.36    39.1 1203.32    78.2 1192.07
    97.8 1188.82   107.6 1185.07   136.9 1169.15   156.4 1153.37   166.2 1147.54
   185.8 1136.79   205.3 1128.49   244.4 1103.63     264  1093.4   283.5 1086.62
   312.9 1082.45   332.4 1077.04   351.5 1074.64     352 1074.59   366.5 1075.99
   381.3 1079.12   400.8 1080.91   420.4 1100.51   449.7 1121.95   469.3 1133.06
   518.2 1157.31   557.3 1183.76   625.7 1221.92   645.3 1230.71   664.8 1243.43
#Mann= 3 , 0 , 0
       0      .1       0   351.5    .045       0   366.5      .1       0
Bank Sta=351.5,366.5
XS Rating Curve= 0 ,0
Exp/Cntr=0.3,0.1

Type RM Length L Ch R = 1 ,29366.6 ,345.2,345.2,345.2
XS GIS Cut Line= 2
     1721134.516      300661.056     1721808.291      300860.393
#Sta/Elev= 30
       0  1262.2     9.8 1251.11    58.6 1225.14    78.1 1213.82    87.8 1207.75
    97.6 1198.19   107.4 1190.84   117.1  1186.3   126.9 1180.55   146.4 1164.17
   175.7 1137.35   195.2 1121.76   204.9 1109.51   234.2 1095.02   273.2  1078.3
   292.8 1073.81   312.3 1067.76   320.1 1066.82   331.8 1066.53   335.1 1066.72
   468.4 1075.78     488  1078.1   497.7 1080.98   507.5 1088.15   517.2 1097.28
   556.3 1124.86     605  1162.1   614.8 1175.16   634.3 1188.79   702.6 1232.65
#Mann= 3 , 0 , 0
       0      .1       0   320.1    .045       0   335.1      .1       0
Bank Sta=320.1,335.1
XS Rating Curve= 0 ,0
Exp/Cntr=0.3,0.1

Type RM Length L Ch R = 1 ,29021.1 ,346.8,346.8,346.7
XS GIS Cut Line= 2
     1721063.426      300998.914     1721684.896      301182.775
#Sta/Elev= 30
       0 1213.33     9.8 1204.23    19.6 1197.99    39.3 1189.39    58.9 1185.14
    68.7 1181.63    78.6 1175.52    98.2 1161.33     108 1152.22   117.8 1140.69
   196.4 1083.19     216 1070.14   245.5 1067.46   294.6 1067.34   304.4 1065.52
   316.7 1060.28     324 1057.85   331.7 1058.85   353.5 1065.64   363.3 1067.49
   392.8 1069.72   412.4 1073.14   422.2 1076.87   481.2 1102.89   530.3 1126.86
   569.5 1142.63   608.8 1160.32   618.6 1164.99   628.5 1173.94   648.1  1183.8
#Mann= 3 , 0 , 0
       0      .1       0   316.7    .045       0   331.7      .1       0
Bank Sta=316.7,331.7
XS Rating Curve= 0 ,0
Exp/Cntr=0.3,0.1

Type RM Length L Ch R = 1 ,28674.2 ,303.2,302,300.8
XS GIS Cut Line= 2
     1720971.802      301332.339     1721596.627      301517.194
#Sta/Elev= 30
       0 1206.08    29.2 1191.48    38.9 1185.09    48.6 1177.19    77.8 1169.46
    87.5 1165.81   116.7 1145.62   136.2  1129.7   145.9 1117.34   155.6 1109.23
   165.3 1104.24   194.5  1091.3   243.1 1073.87   252.9 1068.38   291.8 1060.67
   316.5 1051.83   330.7 1050.73   331.5 1050.86   340.4 1052.36   350.1 1056.08
   359.8 1058.33   437.6 1058.13   447.4 1059.63   457.1 1066.29   486.3  1078.8
   544.6 1107.09   564.1 1122.68   612.7  1151.3   632.2  1164.5   651.6 1179.19
#Mann= 3 , 0 , 0
       0      .1       0   316.5    .045       0   331.5      .1       0
Bank Sta=316.5,331.5
XS Rating Curve= 0 ,0
Exp/Cntr=0.3,0.1

Type RM Length L Ch R = 1 ,28372   ,196,195.6,195.2
XS GIS Cut Line= 2
      1720847.79      301625.062     1721485.972      301780.676
#Sta/Elev= 30
       0 1252.48     9.8 1241.44    19.6 1234.54      98 1183.76   107.8 1175.07
   117.6 1168.03   137.3 1157.74   186.3 1125.59   196.1  1117.7   205.9 1107.27
   225.5 1093.81   245.1  1082.1   264.7 1072.02   294.1  1059.7   303.9 1056.47
   323.5 1053.89   362.8 1042.67   367.3  1042.7   382.3 1044.72     402 1050.42
   470.6  1052.7   490.2 1059.68     500 1065.79   509.8 1074.82   539.2 1091.92
   568.6 1111.85   598.1 1130.18   607.9 1141.09   617.7 1147.76   656.9 1171.61
#Mann= 3 , 0 , 0
       0      .1       0   367.3    .045       0   382.3      .1       0
Bank Sta=367.3,382.3
XS Rating Curve= 0 ,0
Exp/Cntr=0.3,0.1

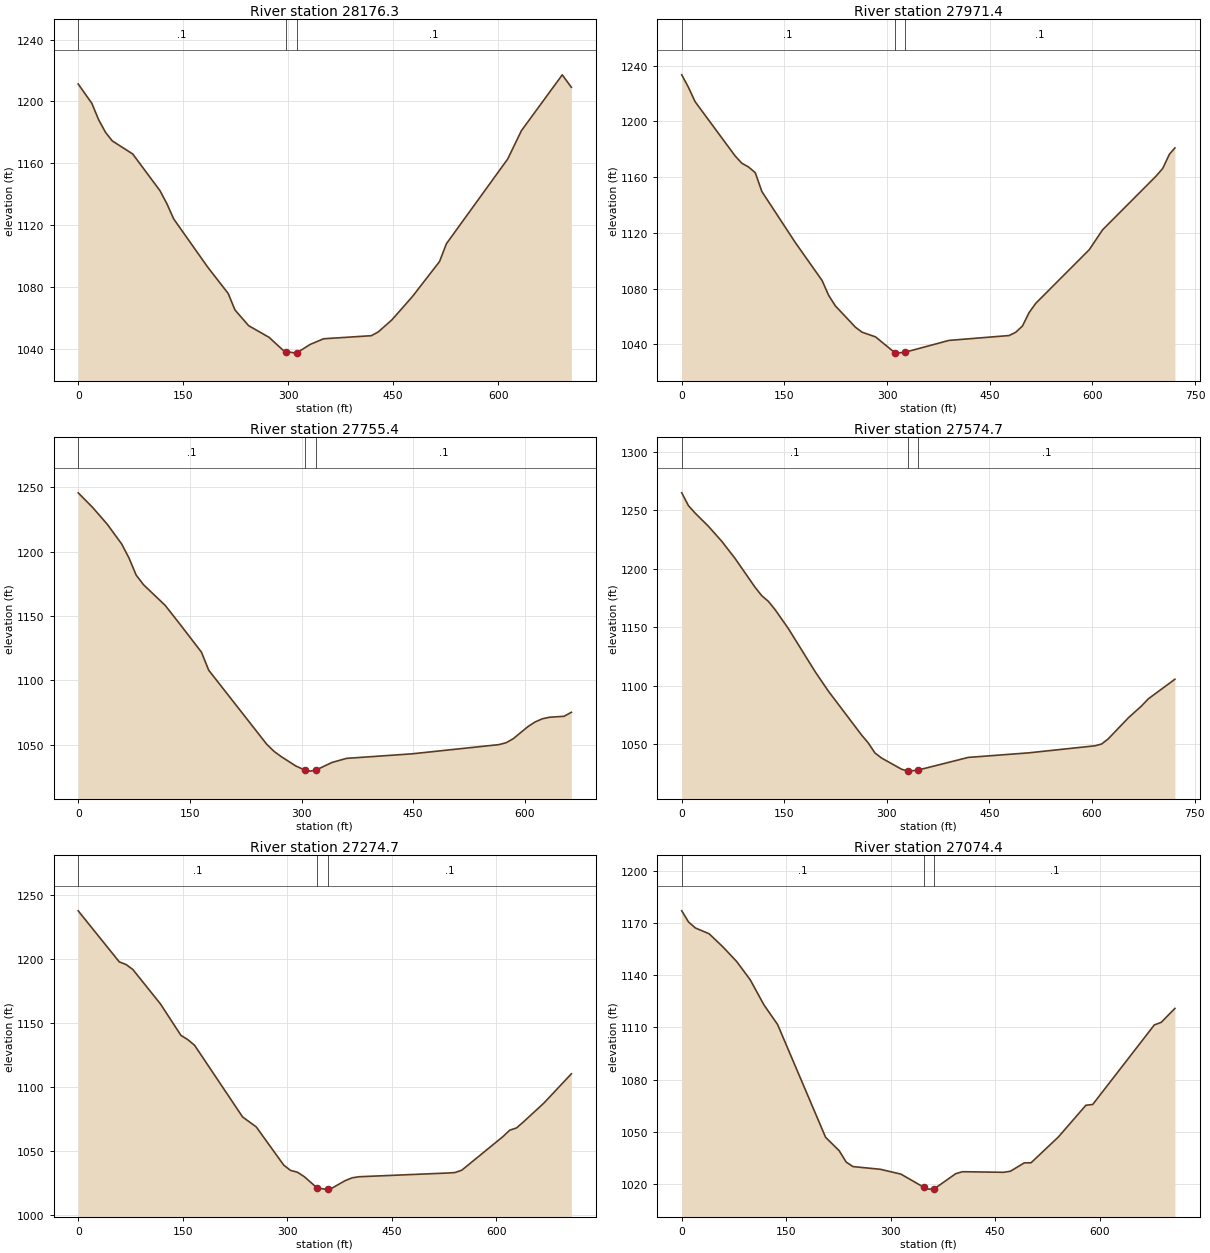
Type RM Length L Ch R = 1 ,28176.3 ,204.8,204.8,204.8
XS GIS Cut Line= 3
     1720847.118       301828.84     1721521.902      301980.131
     1721509.151      301982.628
#Sta/Elev= 30
       0 1211.27    19.5 1198.77    29.2 1188.19      39 1180.06    48.7  1174.5
    77.9 1166.06   116.9 1142.32   126.6 1134.04   136.4 1124.13   185.1 1092.94
   214.3 1075.93     224  1065.3   243.5 1055.15   272.7 1047.64   292.2  1039.5
   297.2 1038.44   311.7 1037.44   312.2 1037.59   331.2 1043.02   350.6 1046.71
   418.8  1048.7   428.6 1051.12     448 1058.86   477.3  1073.9   516.2  1096.6
     526 1108.11   613.6 1162.84   633.1 1181.09   691.5 1217.19   704.5 1209.14
#Mann= 3 , 0 , 0
       0      .1       0   297.2    .045       0   312.2      .1       0
Bank Sta=297.2,312.2
XS Rating Curve= 0 ,0
Exp/Cntr=0.3,0.1

Type RM Length L Ch R = 1 ,27971.4 ,216,216,215.9
XS GIS Cut Line= 3
     1720784.238      302024.192     1721479.513      302180.077
     1721487.371      302178.538
#Sta/Elev= 30
       0 1233.42     9.8 1224.47    19.5 1214.16    78.1 1175.12    87.8 1169.96
    97.6 1167.27   107.4 1163.17   117.1 1149.61   165.9 1113.02     205  1085.8
   214.7 1075.04   224.5  1067.5   253.8 1052.19   263.5 1048.62   283.1 1045.29
     311 1034.06   312.3 1033.61     326 1034.23   390.4 1042.74   478.3 1046.24
     488 1048.59   497.8 1053.11   507.6 1062.78   517.3 1069.41   595.4 1107.89
   614.9 1122.19     693 1160.71   702.8  1166.3   712.5 1176.44   720.5 1180.94
#Mann= 3 , 0 , 0
       0      .1       0     311    .045       0     326      .1       0
Bank Sta=311,326
XS Rating Curve= 0 ,0
Exp/Cntr=0.3,0.1

Type RM Length L Ch R = 1 ,27755.4 ,169.7,180.5,191.3
XS GIS Cut Line= 2
     1720746.591      302235.313     1721392.894      302380.219
#Sta/Elev= 30
       0 1245.73    19.5 1234.31      39 1221.35    58.4 1206.01    68.2 1195.11
    77.9 1181.79    87.7 1174.37   116.9 1158.27   136.4  1143.9   165.6 1121.93
   175.3 1107.95   253.2 1050.45     263 1044.94   272.7 1040.82   292.2 1033.57
   304.8 1030.28   311.7 1029.55   319.8 1030.49   340.9 1036.28   360.4 1039.46
   448.1 1042.97   564.9 1050.13   574.7 1051.58   584.4 1054.76   603.9 1064.05
   613.6 1067.72   623.4 1070.19   633.1 1071.41   652.6 1072.14   662.4 1075.26
#Mann= 3 , 0 , 0
       0      .1       0   304.8    .045       0   319.8      .1       0
Bank Sta=304.8,319.8
XS Rating Curve= 0 ,0
Exp/Cntr=0.3,0.1

Type RM Length L Ch R = 1 ,27574.7 ,291.3,300,308.6
XS GIS Cut Line= 2
     1720722.393      302251.944     1721275.343      302714.921
#Sta/Elev= 30
       0    1265     9.8 1254.03    19.5 1247.72      39  1236.4    58.5 1223.61
      78 1208.88   107.2 1184.29     117 1177.05   126.7 1172.23   136.4 1165.22
   155.9 1148.97   194.9 1112.28   214.4  1095.5   263.1 1057.88   272.9 1051.08
   282.6 1042.58   292.4 1038.21   321.6 1028.67   330.4 1027.24   331.4 1027.08
   345.4 1027.96   419.1 1038.81   506.8 1042.67   604.2 1048.72     614 1050.26
   623.7 1054.66     653 1072.59   672.4 1082.79   682.2 1088.83   721.2 1105.63
#Mann= 3 , 0 , 0
       0      .1       0   330.4    .045       0   345.4      .1       0
Bank Sta=330.4,345.4
XS Rating Curve= 0 ,0
Exp/Cntr=0.3,0.1

Type RM Length L Ch R = 1 ,27274.7 ,200.3,200.3,200.3
XS GIS Cut Line= 2
     1720587.464       302346.31     1720921.215      302970.573
#Sta/Elev= 30
       0 1237.74      59 1197.78    68.8 1195.71    78.6 1191.73     118 1164.92
   147.5 1140.27   157.3 1136.97   167.1 1132.49     236 1076.42   255.6 1068.62
     295 1038.77   304.8 1034.59   314.6  1033.2   324.4 1029.74   342.9 1020.89
   353.9 1019.94   357.9 1020.19   363.8 1020.56   383.4 1026.63   393.3  1028.8
   403.1 1029.63   530.9 1032.56   540.7 1032.91   550.6 1034.75   609.6    1061
   619.4 1066.05   629.2 1067.84   639.1 1072.54   668.6 1087.35   707.9  1110.2
#Mann= 3 , 0 , 0
       0      .1       0   342.9    .045       0   357.9      .1       0
Bank Sta=342.9,357.9
XS Rating Curve= 0 ,0
Exp/Cntr=0.3,0.1

Type RM Length L Ch R = 1 ,27074.4 ,503.5,510.1,516.8
XS GIS Cut Line= 2
     1720411.088      302440.607      1720744.84      303064.869
#Sta/Elev= 30
       0 1176.97     9.8 1170.53    19.7  1167.1    39.3  1163.8      59 1156.28
    78.6 1147.97    98.3 1137.35     118 1122.92   137.6 1111.64   206.5 1046.81
   226.1 1039.06     236  1032.6   245.8 1029.99   285.1 1028.43   314.6 1025.66
   347.4 1018.12   353.9 1017.03   362.4 1017.18   393.3 1025.91   403.1 1027.04
   462.1  1026.7   471.9 1027.33   491.6 1032.12   501.4 1032.17   540.7 1047.04
   580.1 1065.22   589.9 1065.68   678.4 1111.42   688.2 1112.86   707.9 1120.89
#Mann= 3 , 0 , 0
       0      .1       0   347.4    .045       0   362.4      .1       0
Bank Sta=347.4,362.4
XS Rating Curve= 0 ,0
Exp/Cntr=0.3,0.1