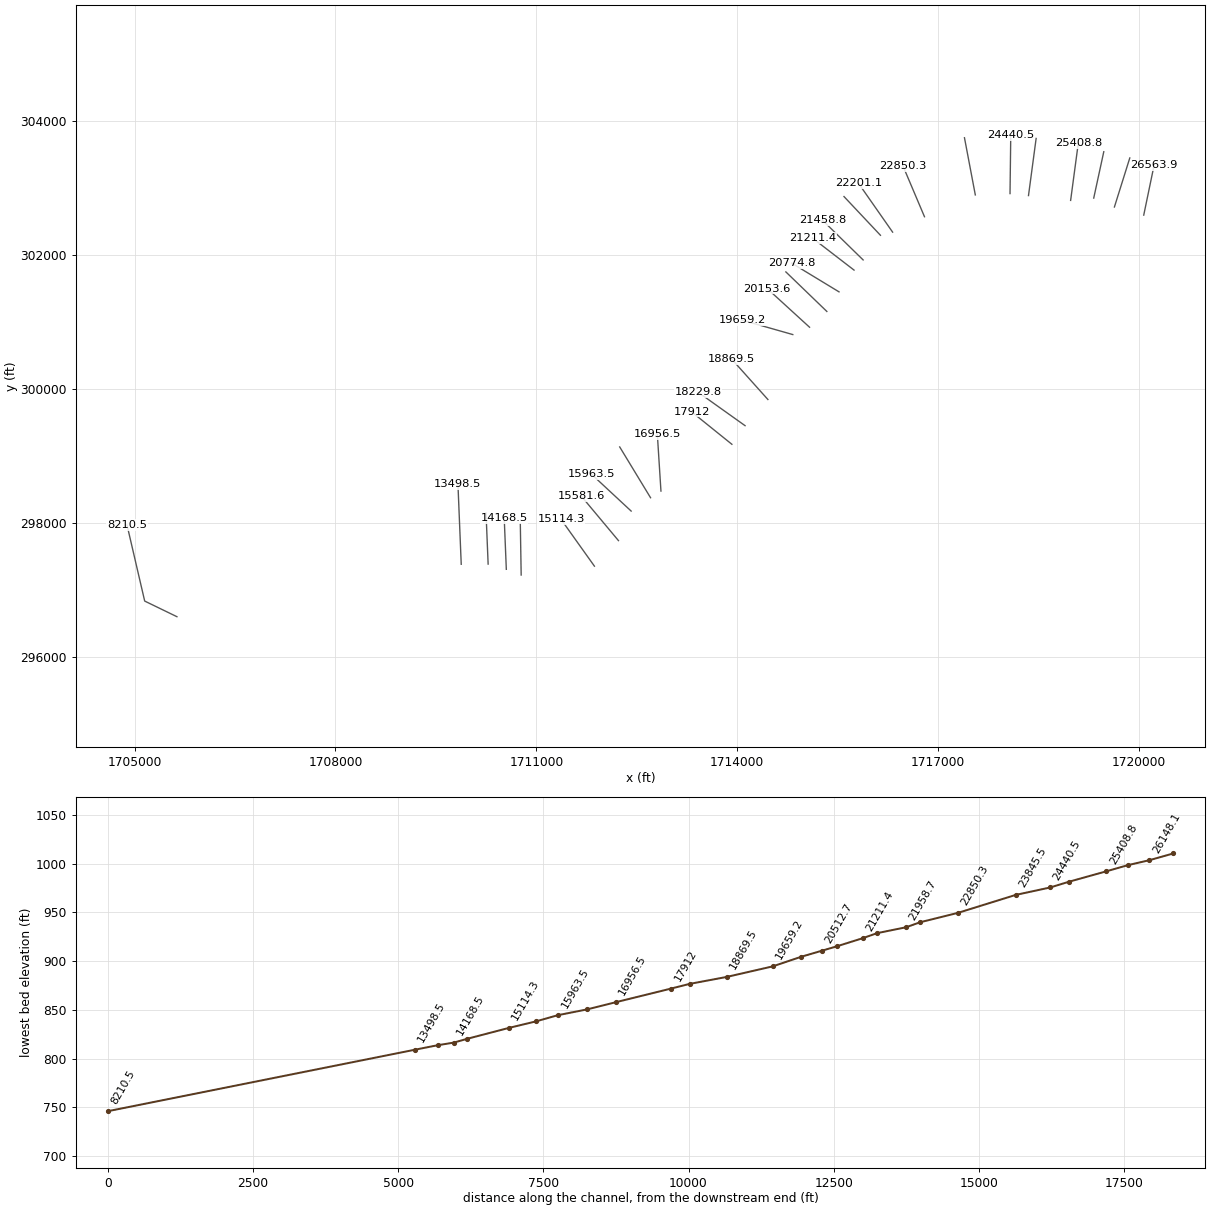
HEC-RAS study RUMCRK.prj: RUMCRK

--- RUMCRK.g01 (geometry) --- (continued)

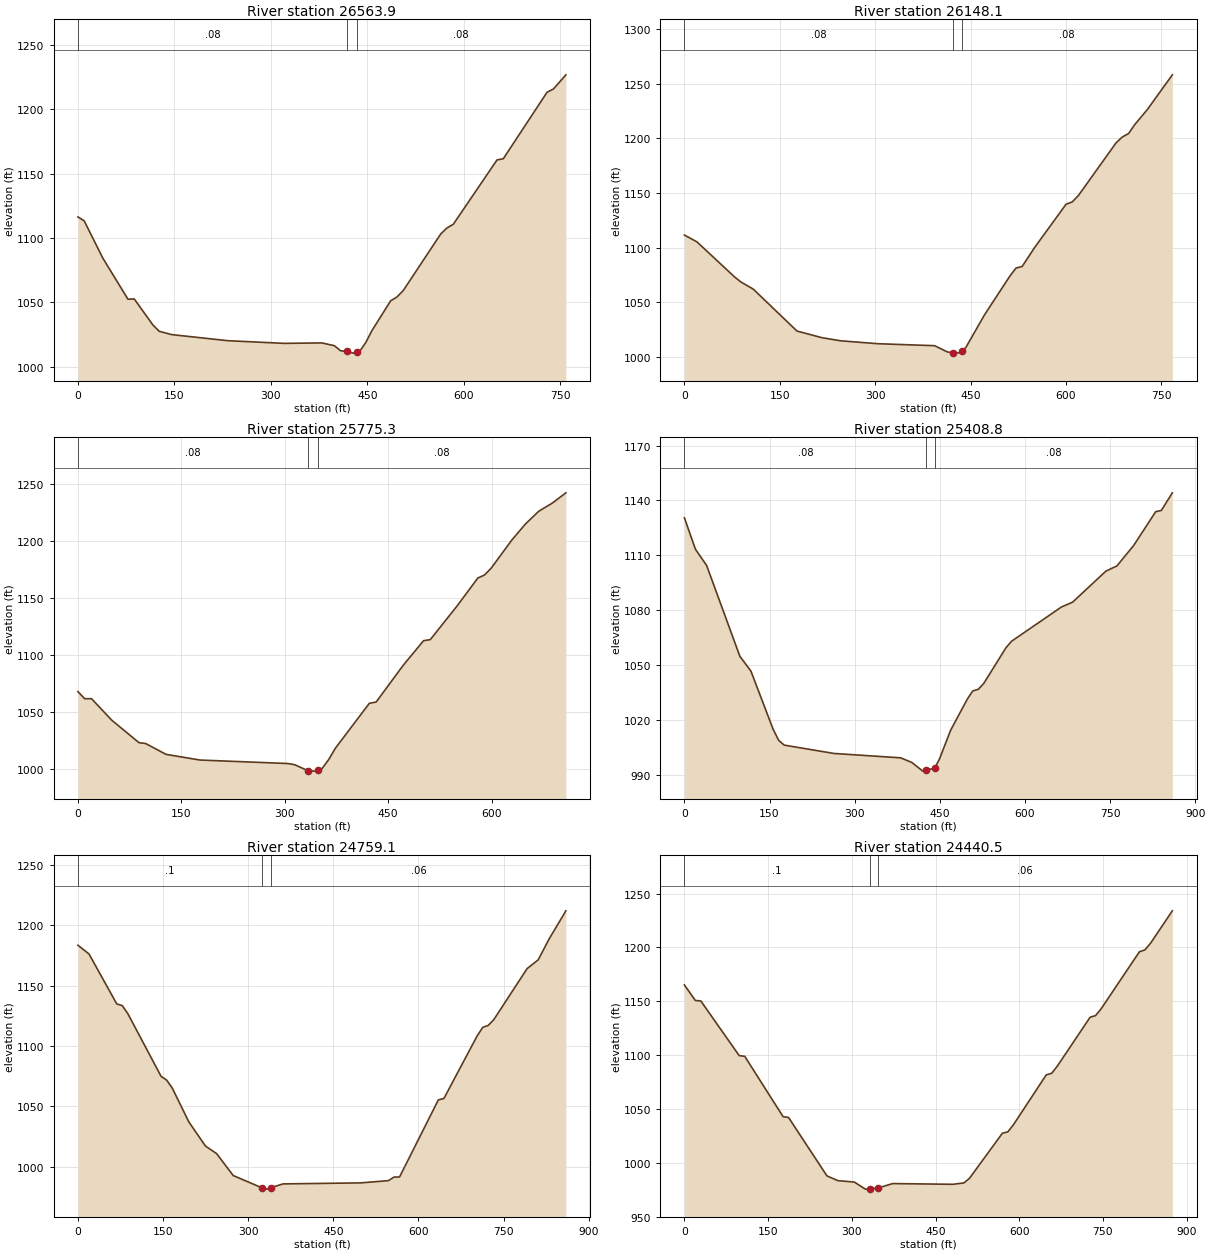
Type RM Length L Ch R = 1 ,26563.9 ,417.9,415.7,413.4
XS GIS Cut Line= 2
     1720070.648      302600.619     1720224.848      303343.139
#Sta/Elev= 30
       0  1116.5     9.7 1113.43    38.9 1084.25    77.8 1052.46    87.5  1052.7
   116.7 1032.34   126.4 1027.54   145.8 1024.95   233.3 1020.22   320.8 1018.15
   379.2  1018.5   398.6 1016.34   408.4 1012.35   418.2 1011.95   427.8 1010.56
   433.2 1011.16   437.5 1011.63   447.2 1018.68     457 1028.11   486.1 1051.28
   495.8  1054.2   505.6 1059.21   563.9 1103.22   573.6  1107.9   583.4 1110.75
   651.4  1160.8   661.1 1161.69   729.2 1213.47   738.9 1215.87   758.4 1226.96
#Mann= 3 , 0 , 0
       0     .08       0   418.2    .045       0   433.2     .08       0
Bank Sta=418.2,433.2
XS Rating Curve= 0 ,0
Exp/Cntr=0.3,0.1

Type RM Length L Ch R = 1 ,26148.1 ,370.6,372.6,374.6
XS GIS Cut Line= 2
     1719632.729      302721.843     1719862.472      303453.838
#Sta/Elev= 30
       0 1111.55    19.7 1105.31    78.7 1073.32    88.5 1068.75   108.2 1062.13
     177 1023.76   216.4 1017.66   245.9 1014.81   304.9 1012.15   393.4 1010.36
   413.1 1004.76   421.7 1003.71   422.9 1003.56   432.8 1003.94   436.7 1005.87
   442.6  1008.8   472.1 1038.78   511.5  1073.8   521.3 1081.33   531.1 1082.84
   550.8 1100.25     600 1139.66   609.8 1141.85   619.7 1147.82   678.7 1195.84
   688.5 1201.19   698.4 1204.37   708.2 1212.61   727.9  1226.3   767.2 1258.04
#Mann= 3 , 0 , 0
       0     .08       0   421.7    .045       0   436.7     .08       0
Bank Sta=421.7,436.7
XS Rating Curve= 0 ,0
Exp/Cntr=0.3,0.1

Type RM Length L Ch R = 1 ,25775.3 ,364.6,366.5,368.3
XS GIS Cut Line= 2
     1719323.897      302854.876     1719473.989      303546.661
#Sta/Elev= 30
       0 1068.11     9.8 1061.91    19.7 1061.94    49.2    1043    88.5 1023.44
    98.3 1022.63   127.8 1013.16     177 1008.18   304.8 1005.11   314.6 1004.06
   333.9  998.76   344.1  998.46   348.9  999.47   353.9 1000.52   363.8  1008.6
   373.6 1018.63   422.8 1057.89   432.6 1058.97   471.9 1091.18   501.4 1112.74
   511.2 1113.69   550.6  1143.6   580.1 1167.61   589.9 1170.34   599.7 1176.43
   629.2  1200.7   648.9 1214.78   668.6 1226.19   688.2  1233.3   707.9  1242.3
#Mann= 3 , 0 , 0
       0     .08       0   333.9    .045       0   348.9     .08       0
Bank Sta=333.9,348.9
XS Rating Curve= 0 ,0
Exp/Cntr=0.3,0.1

Type RM Length L Ch R = 1 ,25408.8 ,649.4,649.4,649.5
XS GIS Cut Line= 2
     1718978.934      302820.027     1719093.017      303672.248
#Sta/Elev= 30
       0 1130.54    19.5 1113.34    39.1 1104.57    97.7 1054.95   117.2 1046.84
   156.3 1015.11   166.1 1009.02   175.9  1006.4   263.8 1001.84   381.1  999.46
   400.6  996.95   420.1   992.2   426.2   992.6   441.2  993.91   449.4  998.79
     469 1014.44   498.3 1031.42   508.1    1036   517.8 1036.88   527.6 1040.14
   566.7 1059.61   576.5 1063.14   664.4 1081.84     684 1084.46   742.6 1101.39
   762.1 1104.26   791.4 1115.32   830.5  1133.9   840.3 1134.54   859.8 1144.18
#Mann= 3 , 0 , 0
       0     .08       0   426.2    .045       0   441.2     .08       0
Bank Sta=426.2,441.2
XS Rating Curve= 0 ,0
Exp/Cntr=0.3,0.1

Type RM Length L Ch R = 1 ,24759.1 ,315.8,318.5,321.2
XS GIS Cut Line= 2
     1718349.681       302892.21     1718463.764      303744.431
#Sta/Elev= 30
       0 1183.42    19.5 1176.16    68.4 1134.82    78.2 1133.36    87.9 1126.75
   146.6 1074.75   156.3  1071.7   166.1  1065.2   195.4 1037.11   224.7 1017.08
   244.3 1010.84   273.6  992.66   324.8  982.37   332.2   981.4   339.8  982.59
   361.5  985.73   498.3  986.57   547.2  988.44   556.9  991.37   566.7  991.46
   635.1 1055.32   644.9  1056.5   703.5 1108.32   713.3  1115.4     723    1117
   732.8 1121.77   791.4 1163.99     811 1171.28   830.5 1188.79   859.8  1211.9
#Mann= 3 , 0 , 0
       0      .1       0   324.8    .045       0   339.8     .06       0
Bank Sta=324.8,339.8
XS Rating Curve= 0 ,0
Exp/Cntr=0.3,0.1

Type RM Length L Ch R = 1 ,24440.5 ,590.5,595,599.5
XS GIS Cut Line= 2
     1718073.856      302921.806     1718084.921      303796.111
#Sta/Elev= 30
       0 1165.18    19.6 1150.74    29.5 1150.26    98.2 1099.55   108.1 1098.92
   176.8 1042.92   186.7 1042.09   255.4  987.91   275.1  983.46   304.6  982.16
   324.2   975.6   332.3  975.68   347.3  976.72   373.3  980.75   481.4  980.08
     501  981.38   510.9  985.65   569.8 1027.48   579.6 1028.78   589.5 1035.27
   648.4 1081.65   658.2 1083.17   668.1 1089.68     727 1135.14   736.8  1136.7
   746.7 1142.93   815.4 1195.96   825.2  1197.7   835.1 1203.72   874.4 1233.96
#Mann= 3 , 0 , 0
       0      .1       0   332.3    .045       0   347.3     .06       0
Bank Sta=332.3,347.3
XS Rating Curve= 0 ,0
Exp/Cntr=0.3,0.1

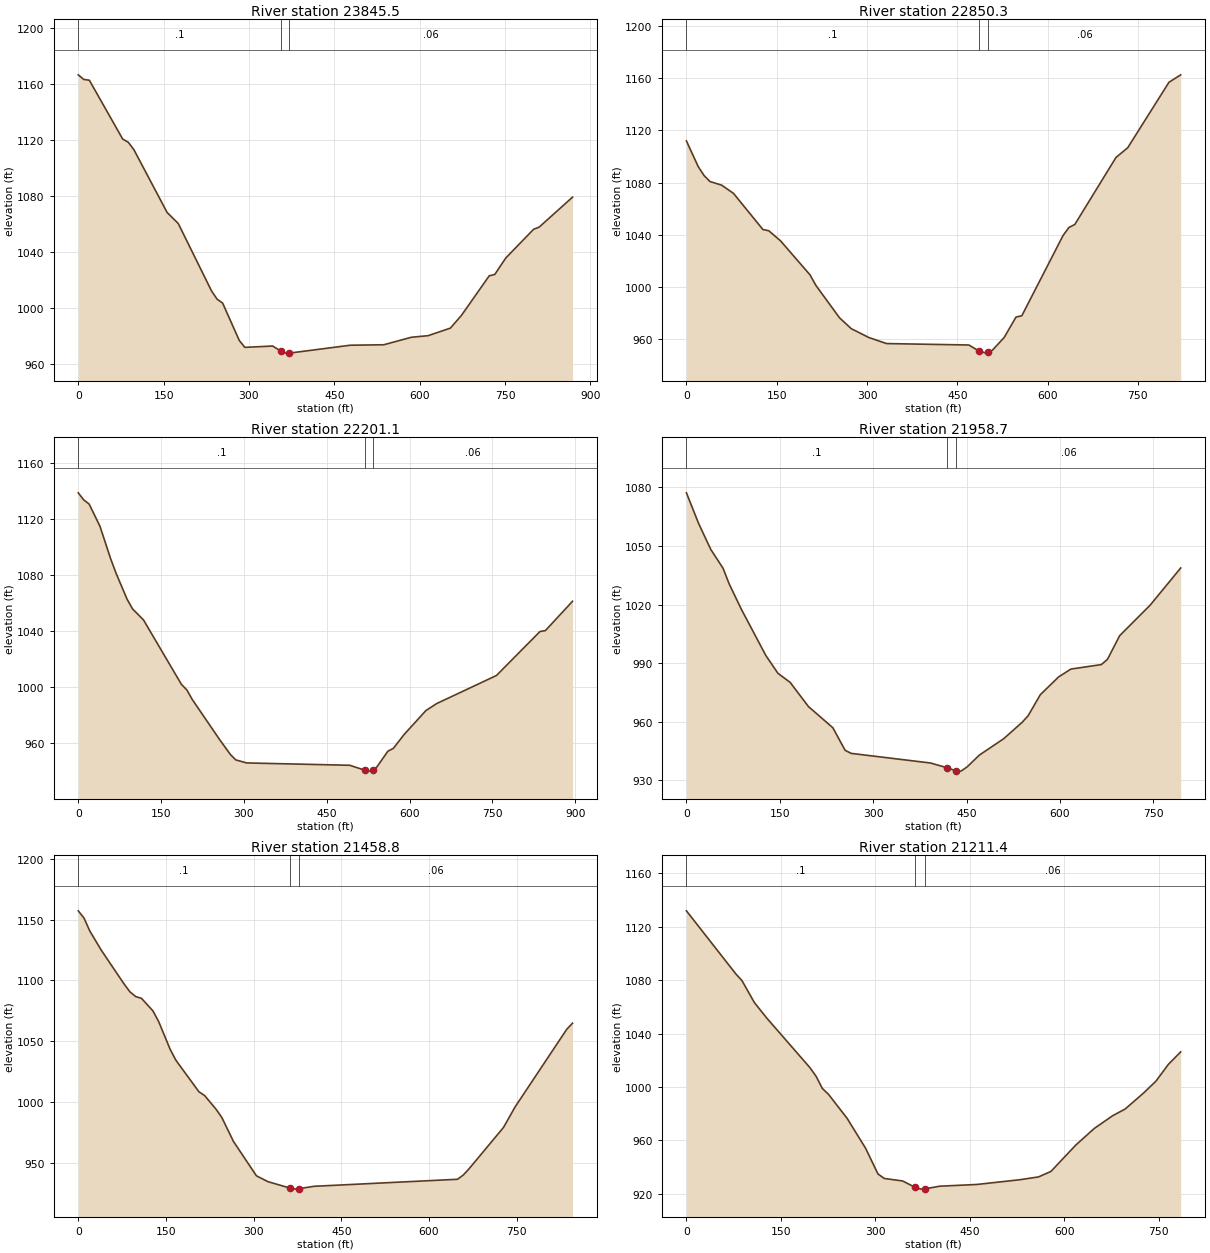
Type RM Length L Ch R = 1 ,23845.5 ,989.1,993.8,995.3
XS GIS Cut Line= 2
     1717555.523      302902.029     1717393.603       303755.36
#Sta/Elev= 30
       0 1166.34     9.8 1163.05    19.5 1162.49    78.1 1120.55    87.8  1118.3
    97.6  1113.1   156.2 1068.19   175.7 1060.38   234.2  1012.3     244  1006.4
   253.7 1003.63     283  976.97   292.8  972.05   341.6     973   355.9   969.4
   361.1  968.04   370.8  967.94   370.9  967.95   478.2  973.58   536.8   973.9
   585.5  979.26   614.8  980.38   653.9  985.76   673.4  994.85   722.2 1023.05
   731.9    1024   751.4 1035.81   800.2 1056.22     810 1057.78   868.6 1079.14
#Mann= 3 , 0 , 0
       0      .1       0   355.9    .045       0   370.9     .06       0
Bank Sta=355.9,370.9
XS Rating Curve= 0 ,0
Exp/Cntr=0.3,0.1

Type RM Length L Ch R = 1 ,22850.3 ,644.4,649,653.7
XS GIS Cut Line= 2
     1716796.581      302576.378     1716476.096      303332.366
#Sta/Elev= 30
       0 1111.89    19.6 1092.24    29.3 1085.42    39.1 1080.83    58.6 1078.05
    78.2 1071.76   127.1 1044.09   136.8 1043.18   156.4 1035.42   205.3 1009.43
     215  1001.4   254.2  976.62   273.7  968.27     303  961.48   332.4  956.84
   469.2  955.74   486.3  951.05   498.5  949.52   501.3  950.16   508.3  951.77
   527.9  961.51   547.4  977.06   557.2  978.14   625.6 1039.46   635.4 1045.66
   645.2 1047.97   713.6 1099.26   733.1 1106.69   801.6 1156.78   821.1 1162.48
#Mann= 3 , 0 , 0
       0      .1       0   486.3    .045       0   501.3     .06       0
Bank Sta=486.3,501.3
XS Rating Curve= 0 ,0
Exp/Cntr=0.3,0.1

Type RM Length L Ch R = 1 ,22201.1 ,239,242.3,245.6
XS GIS Cut Line= 2
      1716320.63      302346.705     1715807.882      303080.181
#Sta/Elev= 30
       0 1138.56     9.8 1133.59    19.7 1130.54    39.3  1114.7      59 1091.11
    68.8 1080.83    88.5 1062.59    98.3  1055.7     118 1047.93   186.8 1001.85
   196.7  997.84   206.5  991.02   255.7  962.59   275.4  951.83   285.2  947.94
   304.9  945.78   491.7   944.1   519.5  940.49   531.1  939.93   534.5     941
   540.9  943.02   560.6  954.17   570.4  956.14   590.1  966.12   629.4  983.14
   649.1  988.18   757.2 1008.19   835.9 1039.54   845.8 1040.24   894.9 1061.16
#Mann= 3 , 0 , 0
       0      .1       0   519.5    .045       0   534.5     .06       0
Bank Sta=519.5,534.5
XS Rating Curve= 0 ,0
Exp/Cntr=0.3,0.1

Type RM Length L Ch R = 1 ,21958.7 ,498.9,499.8,500.7
XS GIS Cut Line= 2
     1716138.946      302299.795     1715594.646      302877.603
#Sta/Elev= 30
       0 1077.19    19.6 1061.49    39.2 1048.18    58.8 1038.61    68.6 1030.63
    88.2 1017.62   127.4  994.03     147  984.83   166.6   980.2     196  967.82
   235.2  956.98   254.8  945.47   264.6  943.87     392  938.95   418.5  936.52
   433.5  934.86     441  934.79   450.8  936.97   470.4  942.98   509.6  951.39
     539  959.72   548.8  963.15   568.4  973.92   597.8  983.02   617.4     987
   666.4  989.31   676.2     992   695.8  1004.1   744.8 1019.74   793.8 1038.74
#Mann= 3 , 0 , 0
       0      .1       0   418.5    .045       0   433.5     .06       0
Bank Sta=418.5,433.5
XS Rating Curve= 0 ,0
Exp/Cntr=0.3,0.1

Type RM Length L Ch R = 1 ,21458.8 ,244.7,247.3,250
XS GIS Cut Line= 2
     1715880.408      301931.715     1715275.481      302522.492
#Sta/Elev= 30
       0 1157.14     9.8 1151.25    19.7 1140.66    39.3  1124.9    78.7  1096.9
    88.5 1090.61    98.3 1086.76   108.2 1085.32   127.8 1075.02   137.6 1066.22
   157.3 1043.41   167.1 1034.48   206.5  1008.6   216.3 1005.48     236  994.16
   245.8  987.39   265.5  967.88   304.8  939.68   324.5  934.88     362  929.62
   373.6  928.73     377  929.03   403.1  931.04   648.9  936.82   658.7  940.29
   668.6  945.42   727.6  979.43   747.2  996.09   835.7 1059.92   845.6 1064.93
#Mann= 3 , 0 , 0
       0      .1       0     362    .045       0     377     .06       0
Bank Sta=362,377
XS Rating Curve= 0 ,0
Exp/Cntr=0.3,0.1

Type RM Length L Ch R = 1 ,21211.4 ,433.9,436.4,438.9
XS GIS Cut Line= 2
     1715744.596      301780.075      1715122.69      302258.896
#Sta/Elev= 30
       0 1131.88    78.5 1084.64    88.3 1079.57   107.9 1063.22   127.5 1051.65
   196.2 1014.46     206 1007.96   215.8  998.96   225.6  994.55   255.1   976.6
   284.5  954.19   304.1  934.98     314  931.58   343.4  929.67   363.3  924.88
   372.8  923.57   378.3  923.74   402.2  925.76   461.1  927.05   529.8  930.62
   559.2  932.72   578.8   936.8   618.1  956.45   647.5  968.92     677  978.57
   696.6   983.5     726  995.51   745.6  1004.4   765.3 1016.94   784.9  1026.3
#Mann= 3 , 0 , 0
       0      .1       0   363.3    .045       0   378.3     .06       0
Bank Sta=363.3,378.3
XS Rating Curve= 0 ,0
Exp/Cntr=0.3,0.1

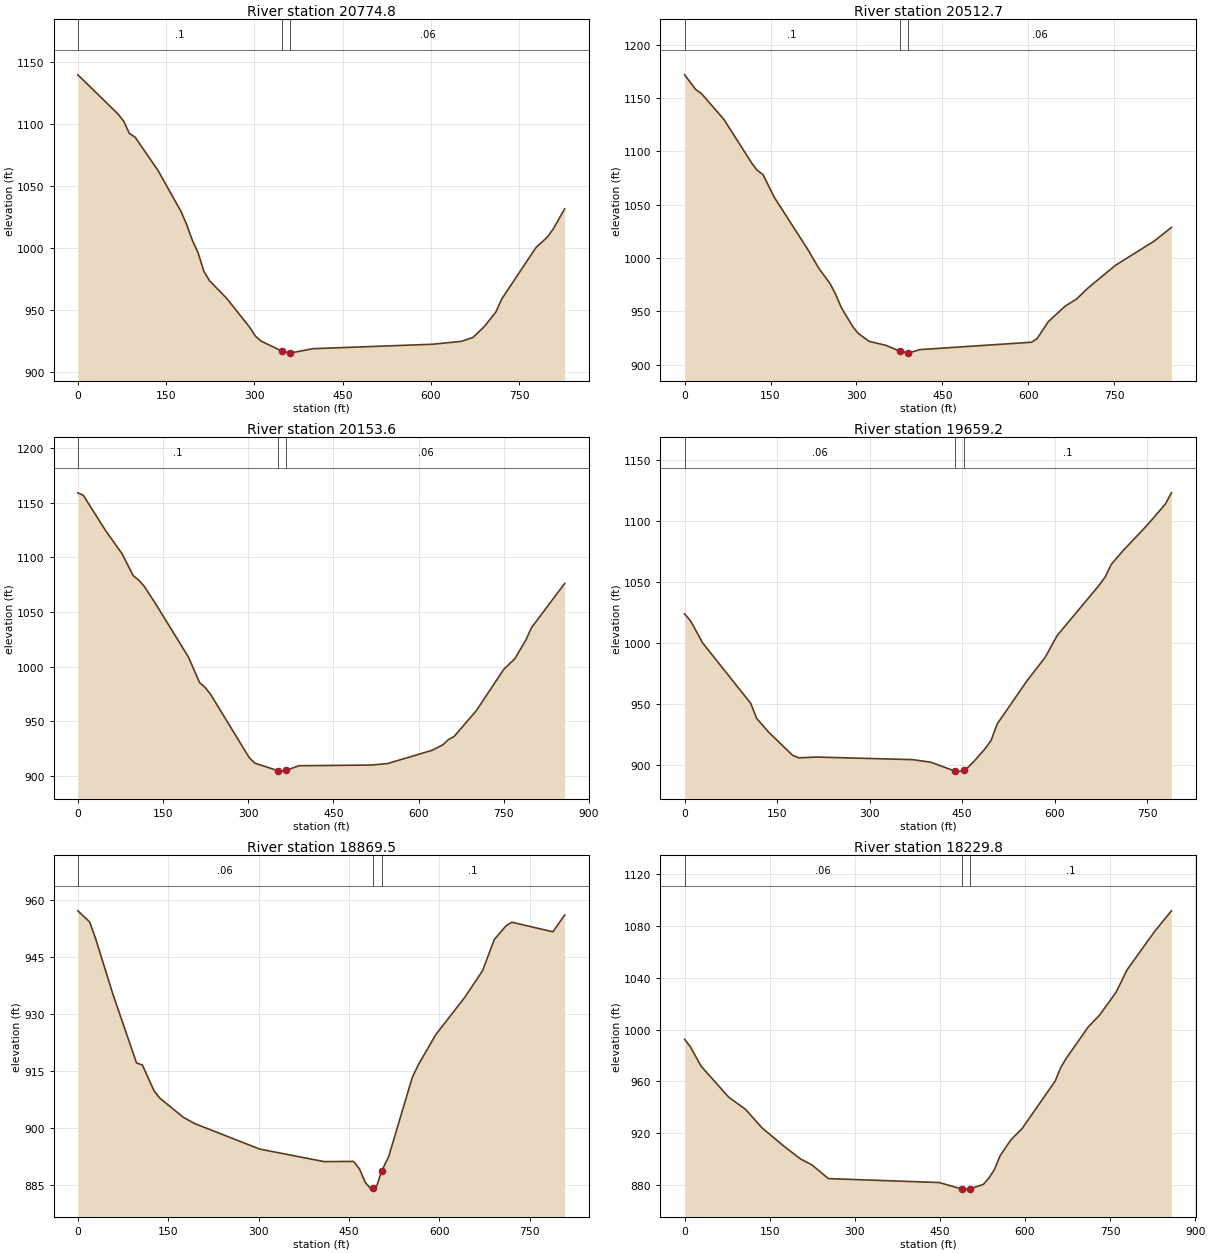
Type RM Length L Ch R = 1 ,20774.8 ,267.2,262.2,257.2
XS GIS Cut Line= 2
     1715520.331      301455.414     1714813.154      301884.295
#Sta/Elev= 30
       0 1139.57    68.1 1108.06    77.8 1102.28    87.6 1092.33    97.3 1089.32
   136.2 1062.52   175.1  1029.6   184.9 1018.91   194.6 1006.15   204.3  996.19
   214.1  981.26   223.8  973.63     253  959.46   291.9   936.2   301.6   929.1
   311.4   925.1   346.1  917.12     360  915.38   361.1  915.45   398.9  918.95
   603.3  922.55   651.9  924.87   671.4     928   690.8  936.91   710.3  948.59
     720  958.86   778.4 1000.45   797.9 1008.95   807.6 1015.36   827.1 1031.62
#Mann= 3 , 0 , 0
       0      .1       0   346.1    .045       0   361.1     .06       0
Bank Sta=346.1,361.1
XS Rating Curve= 0 ,0
Exp/Cntr=0.3,0.1

Type RM Length L Ch R = 1 ,20512.7 ,358.4,359,359.6
XS GIS Cut Line= 2
     1715338.553      301162.902     1714726.633      301752.936
#Sta/Elev= 30
       0 1171.82    19.5 1157.98    29.3 1154.32    68.4 1130.18   117.2 1089.04
     127 1082.12   136.8  1078.3   156.3 1057.19     215 1008.12   234.5  990.29
     254  975.98   263.8  965.84   273.6  953.55   293.1  936.08   302.9  929.38
   322.4  921.82   351.8  918.02   375.5  912.69   390.5   910.8   390.8  910.78
   410.4  914.05   605.8     921   615.6  924.49   635.1  940.33   664.4  954.82
     684  961.35   703.5  971.46   752.3  993.13   820.7 1016.14     850  1028.7
#Mann= 3 , 0 , 0
       0      .1       0   375.5    .045       0   390.5     .06       0
Bank Sta=375.5,390.5
XS Rating Curve= 0 ,0
Exp/Cntr=0.3,0.1

Type RM Length L Ch R = 1 ,20153.6 ,483.6,494.4,505.2
XS GIS Cut Line= 2
     1715080.259      300927.519     1714447.157      301505.352
#Sta/Elev= 30
       0 1159.08     9.7 1156.75    48.7  1124.6    77.9  1103.3    97.4 1083.33
   107.1 1079.34   116.9 1073.53   136.4 1057.99   194.8 1008.76   214.3  985.52
     224  981.16   233.8  974.66     302  916.65   311.7  911.82   351.8     905
   360.4  904.52   366.8  905.33   389.6  909.46   516.2  910.08   545.5  911.46
   623.4  923.51   642.9  928.65   652.6   933.4   662.4  936.13   701.3  959.58
     750  997.62   769.5 1007.38     789 1024.56   798.7 1035.65   857.2 1076.17
#Mann= 3 , 0 , 0
       0      .1       0   351.8    .045       0   366.8     .06       0
Bank Sta=351.8,366.8
XS Rating Curve= 0 ,0
Exp/Cntr=0.3,0.1

Type RM Length L Ch R = 1 ,19659.2 ,802.4,789.5,776.7
XS GIS Cut Line= 2
     1714829.927      300818.058     1714071.046      301033.827
#Sta/Elev= 30
       0 1023.84     9.7 1018.11    29.2 1000.01   107.1  950.36   116.9  937.87
   136.4  926.58   175.3  907.49   185.1  905.55   214.3  906.17   370.1  904.04
   399.4  901.88     438  894.65   438.3  894.61     448  894.65     453  895.84
   457.8  896.99   467.5  901.79     487  913.02   496.8  919.84   506.5  933.28
   555.2  969.02   584.4  988.14   603.9 1006.08   672.1 1047.55   681.8 1054.25
   691.6 1064.58     711 1076.01     750 1096.92   779.2  1114.1     789 1123.35
#Mann= 3 , 0 , 0
       0     .06       0     438    .045       0     453      .1       0
Bank Sta=438,453
XS Rating Curve= 0 ,0
Exp/Cntr=0.3,0.1

Type RM Length L Ch R = 1 ,18869.5 ,634.5,639.3,644
XS GIS Cut Line= 2
     1714458.328       299848.95     1713918.665      300450.702
#Sta/Elev= 30
       0  957.18    19.5  954.26    29.2  949.98    58.4  935.08    97.4  917.08
   107.1  916.53   126.6   909.7   136.3  907.76   175.3  902.73   194.8  901.04
   301.9  894.37     409  891.06   457.7  891.12   467.4   889.2   477.2  885.58
   486.9  883.81   489.3  884.06   496.7  884.83   504.3  888.53   516.1   892.4
   555.1  913.16   564.8  916.44     594  924.48   642.7  934.43     672  941.39
   691.4   949.6   710.9  953.22   720.6  954.18   788.8  951.65   808.3  956.08
#Mann= 3 , 0 , 0
       0     .06       0   489.3    .045       0   504.3      .1       0
Bank Sta=489.3,504.3
XS Rating Curve= 0 ,0
Exp/Cntr=0.3,0.1

Type RM Length L Ch R = 1 ,18229.8 ,319,317.9,316.9
XS GIS Cut Line= 2
     1714117.495      299458.416     1713418.442      299956.098
#Sta/Elev= 30
       0   992.5     9.8  986.94    29.2   971.7      78  947.64   107.3  938.42
   136.5  924.02   175.5   909.7   204.8  899.87   224.3  895.45   253.5   884.8
   448.6  881.78   488.1  876.84   497.3  876.67   503.1   876.9   526.6  880.34
   536.3  885.14   546.1  891.82   555.8  902.15   565.6   908.7   575.3  914.84
   594.8  923.44   653.3  960.27   663.1  970.76   672.8  977.85   711.8 1002.24
   731.4 1011.16   760.6  1028.9   780.1 1046.35   828.9 1076.13   858.1 1091.86
#Mann= 3 , 0 , 0
       0     .06       0   488.1    .045       0   503.1      .1       0
Bank Sta=488.1,503.1
XS Rating Curve= 0 ,0
Exp/Cntr=0.3,0.1

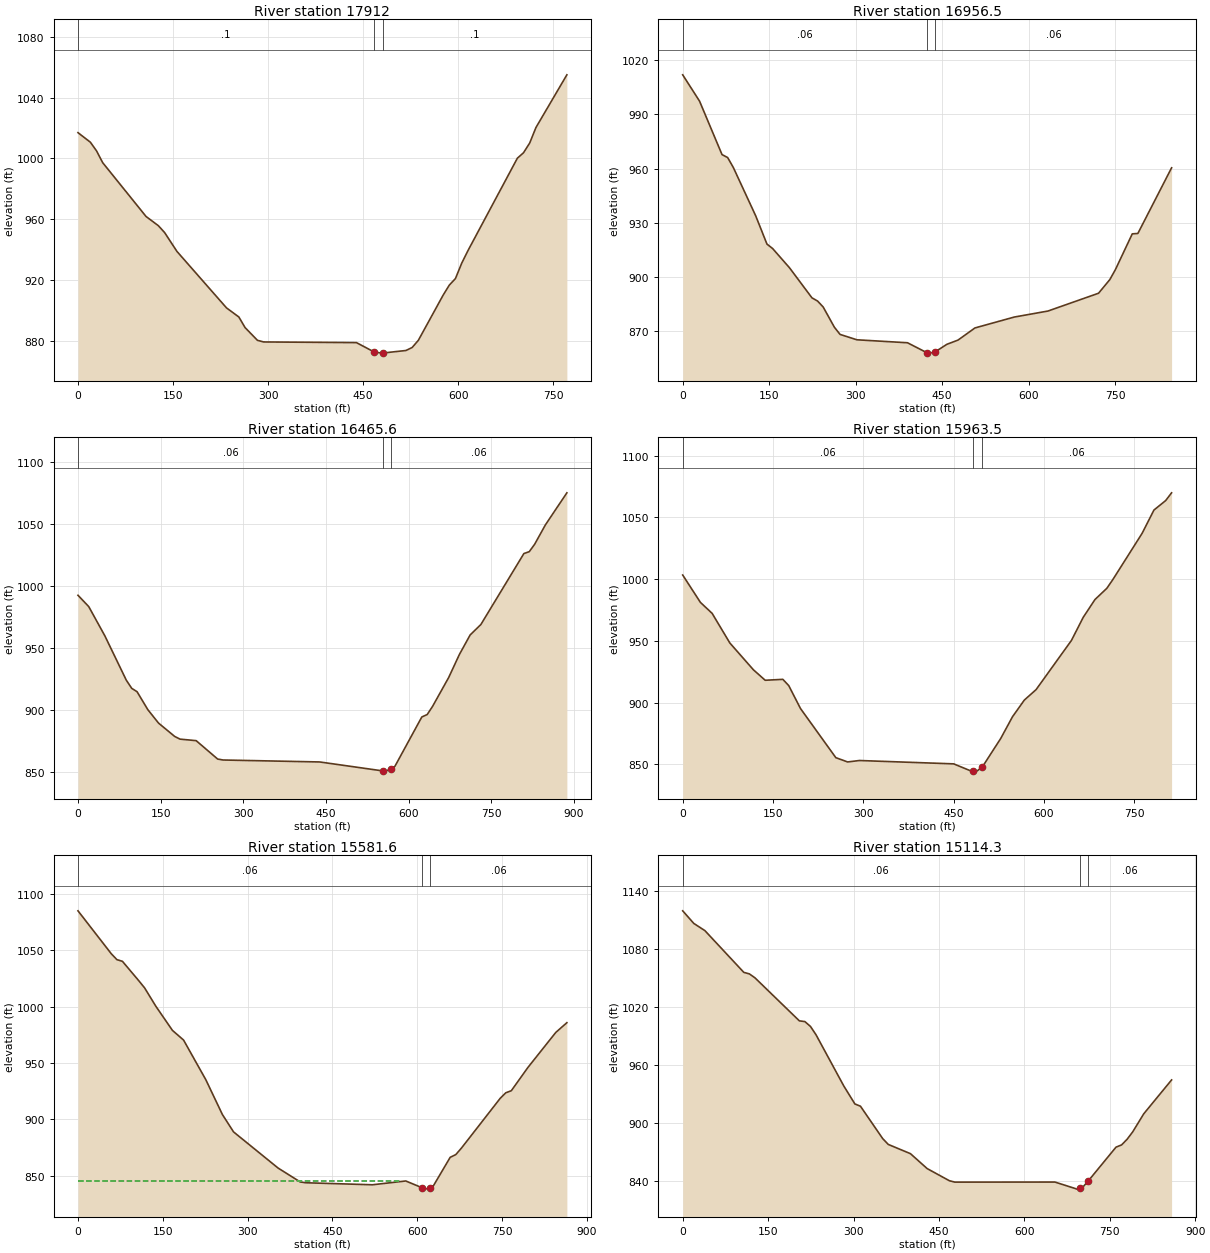
Type RM Length L Ch R = 1 ,17912   ,974.8,954.5,934.2
XS GIS Cut Line= 2
     1713920.524      299180.684     1713319.596      299664.156
#Sta/Elev= 30
       0 1016.94    19.5 1010.68    29.3 1004.94      39  997.19   107.4  961.79
   126.9   955.7   136.7   951.2   156.2  938.77   234.3  901.66   253.8  895.65
   263.6   888.7   283.1  880.32   292.9  879.23   439.3   878.8   466.5  872.81
   478.4  871.88   481.5  871.97   517.4  873.61   527.2  875.58     537  880.32
     576  909.96   585.8  916.63   595.5  920.93   605.3  930.97   615.1  939.21
   693.2 1000.14   702.9 1003.73   712.7 1010.15   722.5 1020.32   771.3    1055
#Mann= 3 , 0 , 0
       0      .1       0   466.5    .045       0   481.5      .1       0
Bank Sta=466.5,481.5
XS Rating Curve= 0 ,0
Exp/Cntr=0.3,0.1

Type RM Length L Ch R = 1 ,16956.5 ,477.7,491.3,504.6
XS GIS Cut Line= 2
     1712861.285      298482.266     1712807.383      299328.765
#Sta/Elev= 30
       0 1011.85    29.2  997.31    68.2  967.72      78  966.07    87.8  960.59
   126.7  933.79   146.2  918.17     156  915.73   185.2  905.11   224.2  888.45
     234  886.66   243.7  883.38   263.2  872.16     273   868.2   302.2  865.22
     390  863.58   423.1  858.17     429  857.84   438.1  858.55   458.2   862.7
   477.7  865.06     507  871.77   575.2   877.8   633.7  881.13   721.5  890.99
     741  898.52   750.7  904.05     780  923.84   789.7  924.06   848.2  960.39
#Mann= 3 , 0 , 0
       0     .06       0   423.1    .045       0   438.1     .06       0
Bank Sta=423.1,438.1
XS Rating Curve= 0 ,0
Exp/Cntr=0.3,0.1

Type RM Length L Ch R = 1 ,16465.6 ,495.8,502,508.3
XS GIS Cut Line= 2
     1712706.026      298383.031     1712245.414      299141.047
#Sta/Elev= 30
       0  992.49    19.5  983.35    48.7  959.79    87.7  923.91    97.5  917.36
   107.2  914.63   126.7  900.15   146.2  889.28   175.4  878.54   185.2  876.35
   214.4  875.12   253.4  860.27   263.2   859.5   438.6  857.92   553.4  850.67
   555.6  850.52   568.4  851.92   575.1  854.48   623.8  894.22   633.6   896.2
   643.3  902.77   672.6  926.12     692  944.69   711.5  960.44     731   968.9
     809 1026.16   818.8  1027.7   828.5 1033.63     848 1049.28     887 1075.19
#Mann= 3 , 0 , 0
       0     .06       0   553.4    .045       0   568.4     .06       0
Bank Sta=553.4,568.4
XS Rating Curve= 0 ,0
Exp/Cntr=0.3,0.1

Type RM Length L Ch R = 1 ,15963.5 ,384.6,381.8,379
XS GIS Cut Line= 2
     1712416.303      298183.902     1711821.473      298736.508
#Sta/Elev= 30
       0 1003.32    29.4  981.18    48.9  972.28    78.3   948.3   117.4  926.63
     137  918.13   166.3  918.88   176.1  913.82   195.6  895.27   254.3  855.49
   273.9  852.02   293.5  853.18     450  850.47   479.3  844.59   482.6  844.67
   489.1  844.83   497.6  847.96   528.2  871.07   547.8  888.69   567.4  902.12
   586.9  910.58   645.6  950.39   665.2  969.11   684.7  983.51   704.3  992.53
   714.1  999.46     763  1037.1   782.6  1055.9   802.1  1063.6   811.9 1069.85
#Mann= 3 , 0 , 0
       0     .06       0   482.6    .045       0   497.6     .06       0
Bank Sta=482.6,497.6
XS Rating Curve= 0 ,0
Exp/Cntr=0.3,0.1

Type RM Length L Ch R = 1 ,15581.6 ,469,467.3,465.6
XS GIS Cut Line= 2
     1712226.821      297743.277     1711672.233      298406.459
#Sta/Elev= 30
       0 1085.21    58.9 1047.11    68.8 1041.89    78.6 1040.39   108.1 1022.81
   117.9 1016.74   137.5 1000.64     167  979.09   186.7  970.49     226  935.35
   255.4  904.36   275.1  888.96   353.7  856.93     393  844.52   402.8  843.82
   520.7  842.02   579.6   845.4   607.6  839.56   618.9  838.16   622.6  839.34
   628.7  841.29   658.2  866.41     668  868.78   677.8  874.42   746.6  918.75
   756.4  923.65   766.3  925.54   795.7  946.22   844.9  977.27   864.5   985.9
#Mann= 3 , 0 , 0
       0     .06       0   607.6    .045       0   622.6     .06       0
#XS Ineff= 2 , 0
           569.3  845.42
Permanent Ineff=
       F       F
Bank Sta=607.6,622.6
XS Rating Curve= 0 ,0
Exp/Cntr=0.3,0.1

Type RM Length L Ch R = 1 ,15114.3 ,725.7,712.1,698.6
XS GIS Cut Line= 2
     1711867.849      297361.875     1711369.171      298060.756
#Sta/Elev= 30
       0 1119.66    19.5 1106.61      39 1099.15   107.3 1055.94   117.1 1054.35
   126.8 1050.32   204.9  1005.7   214.6 1004.95   224.4  999.92   234.2  991.25
   282.9  938.29   302.4  919.65   312.2   917.3   351.2   883.8     361  877.73
     400  868.16   429.3  852.73   468.3  840.15   478.1  838.69   653.7  838.77
   692.7  831.44   697.5  832.36   702.4  833.29   712.5  840.09     761  874.92
   770.8  877.24   780.5   883.1   790.3  890.73   809.8  909.52   858.6  944.54
#Mann= 3 , 0 , 0
       0     .06       0   697.5    .045       0   712.5     .06       0
Bank Sta=697.5,712.5
XS Rating Curve= 0 ,0
Exp/Cntr=0.3,0.1

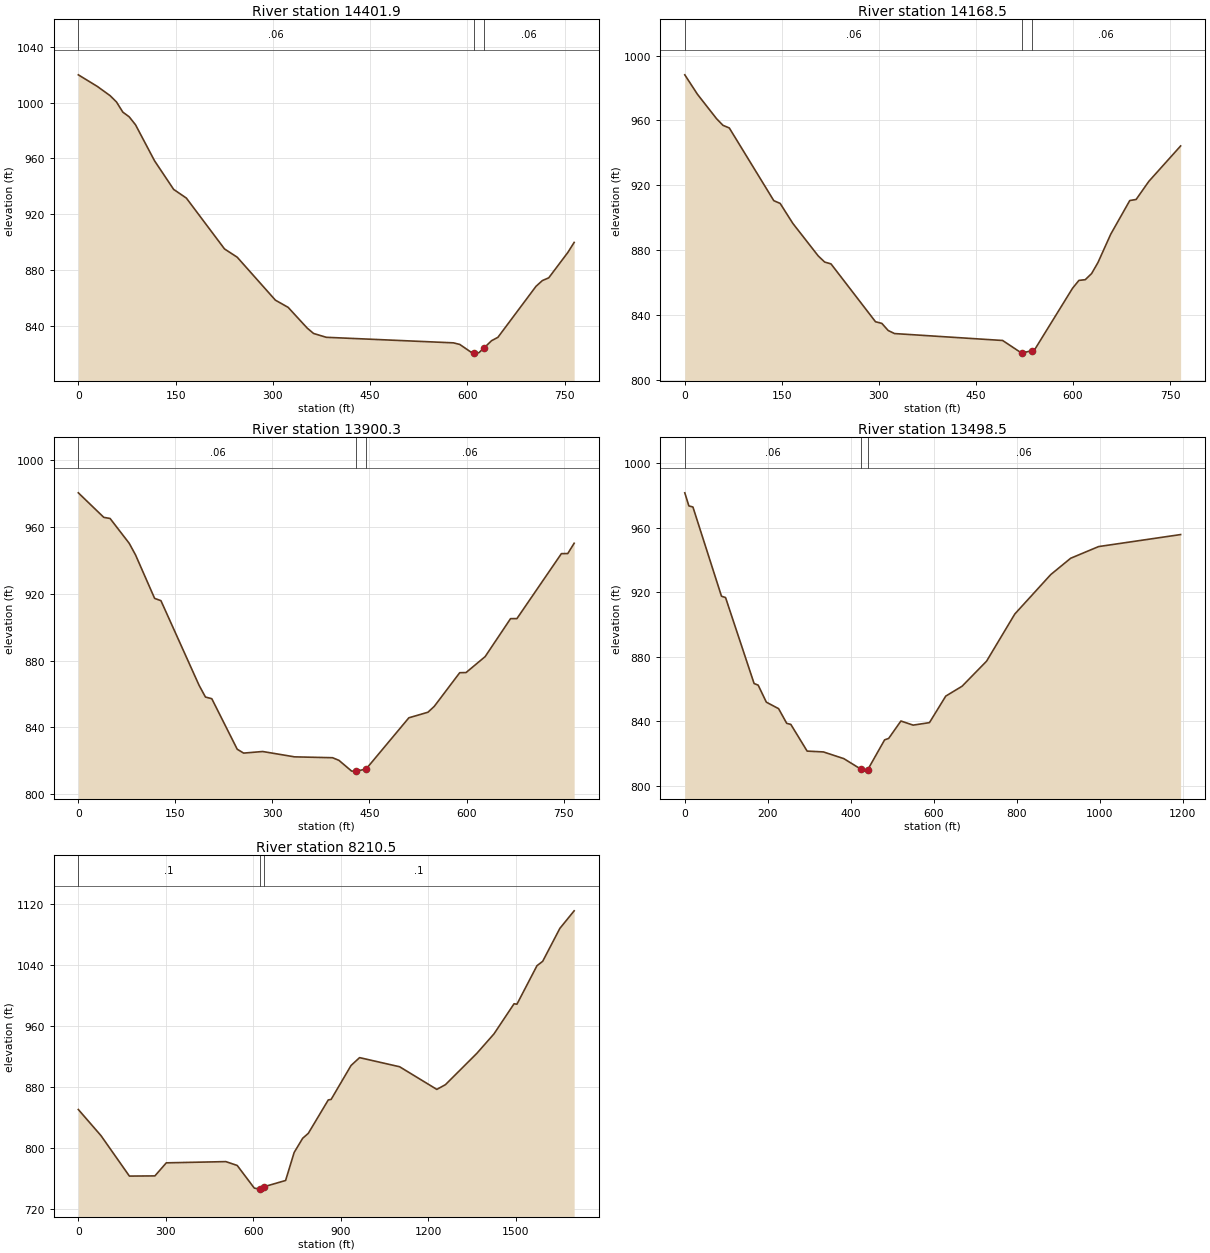
Type RM Length L Ch R = 1 ,14401.9 ,232.8,233.4,233.9
XS GIS Cut Line= 2
     1710774.021      297229.876      1710761.24      297994.306
#Sta/Elev= 30
       0 1019.88    29.4 1011.53      49 1004.94    58.8 1000.44    68.6  993.14
    78.4  989.79    88.2  984.05   117.6  958.18     147  937.73   166.6   931.5
   225.4  895.06     245  889.12   303.8  858.35   323.5  853.18   352.9  838.31
   362.7  834.46   382.3  831.71   578.3  827.73   588.1   826.6   607.7  820.36
   610.5  820.44   617.5  820.63   625.5  824.04   637.1  829.26   646.9  831.67
   705.7  868.27   715.5  872.38   725.3  874.34   754.7  892.49   764.5  899.72
#Mann= 3 , 0 , 0
       0     .06       0   610.5    .045       0   625.5     .06       0
Bank Sta=610.5,625.5
XS Rating Curve= 0 ,0
Exp/Cntr=0.3,0.1

Type RM Length L Ch R = 1 ,14168.5 ,268.3,268.3,268.3
XS GIS Cut Line= 2
      1710552.19      297315.017     1710520.713      298080.735
#Sta/Elev= 30
       0  988.11    19.6  976.09    49.1  961.04      59  956.96    68.8  955.32
   137.6  910.46   147.4  908.78     167  896.45   206.3  876.35   216.2   872.6
     226  871.46   294.8  835.77   304.6  834.75   314.4  830.36   324.2  828.48
   491.3  824.21   520.7  816.41   521.2  816.46   536.2  817.93   540.4  818.32
   599.3  856.41   609.2  861.28     619  861.72   628.8   865.5   638.6  872.27
   658.3  889.73   687.8  910.55   697.6   911.2   717.2  922.35   766.4  944.23
#Mann= 3 , 0 , 0
       0     .06       0   521.2    .045       0   536.2     .06       0
Bank Sta=521.2,536.2
XS Rating Curve= 0 ,0
Exp/Cntr=0.3,0.1

Type RM Length L Ch R = 1 ,13900.3 ,401.7,401.7,401.7
XS GIS Cut Line= 2
     1710280.604      297392.741     1710249.127       298158.46
#Sta/Elev= 30
       0  980.34    39.3  965.68    49.1  964.99    78.6  950.17    88.4  943.22
   117.9  917.21   127.7  915.81   186.7  865.14   196.5  858.18   206.3  857.17
   245.6  826.95   255.5  824.63   284.9  825.59   334.1  822.39     393  821.87
   402.8   820.3   422.5  813.85   429.7  813.86   444.7  815.07   510.9  845.75
   540.4  849.08   550.2   852.6   589.5  872.73   599.3  872.82   628.8  882.35
   668.1  905.07   677.9  905.09   746.7  943.97   756.5     944   766.4  950.17
#Mann= 3 , 0 , 0
       0     .06       0   429.7    .045       0   444.7     .06       0
Bank Sta=429.7,444.7
XS Rating Curve= 0 ,0
Exp/Cntr=0.3,0.1

Type RM Length L Ch R = 1 ,13498.5 ,5282.5,5287.3,5292.1
XS GIS Cut Line= 4
     1709878.892      297390.176     1709847.415      298155.895
     1709837.151      298405.558     1709829.822       298583.85
#Sta/Elev= 30
       0  981.55     9.8  973.46    19.6  972.76    88.4   917.5    98.2  916.66
     167  863.38   176.8  862.39   196.5  851.84     226  847.82   245.6  838.72
   255.5  838.06   294.8  821.52   334.1     821   383.2  816.85   425.5  810.14
   432.3  809.11   440.5  809.85   481.4  828.46   491.3   829.4   520.7  840.16
   550.2  837.62   589.5  839.16   628.8   855.6   668.1  861.71   727.1  877.23
   795.2  906.47   881.7  930.88   929.7     941     997  948.24  1194.7  955.69
#Mann= 3 , 0 , 0
       0     .06       0   425.5    .045       0   440.5     .06       0
Bank Sta=425.5,440.5
XS Rating Curve= 0 ,0
Exp/Cntr=0.3,0.1

Type RM Length L Ch R = 1 ,8210.5  ,255.5,256.7,257.9
XS GIS Cut Line= 4
     1705633.443      296607.625     1705152.021      296841.041
     1705054.764      297259.247     1704888.112      297975.851
#Sta/Elev= 30
       0   850.5    77.8  816.17   175.1  763.14   262.6  763.38   301.6  780.52
   505.8  782.13   544.8  777.08   603.3  747.39   621.2  746.07   622.8  746.03
   636.2  749.11   710.7  757.37     740  794.12   769.2  812.72   788.7  819.31
     857  863.05   866.8  863.75   935.1  908.28   964.4  918.58  1101.7  906.59
  1229.2   876.9  1258.7  883.09  1366.6  924.25  1425.4  949.83  1494.1  989.27
  1503.9  988.68  1572.6  1039.2  1592.2 1044.97  1651.1 1088.19  1700.1 1111.21
#Mann= 3 , 0 , 0
       0      .1       0   621.2    .045       0   636.2      .1       0
Bank Sta=621.2,636.2
XS Rating Curve= 0 ,0
Exp/Cntr=0.3,0.1