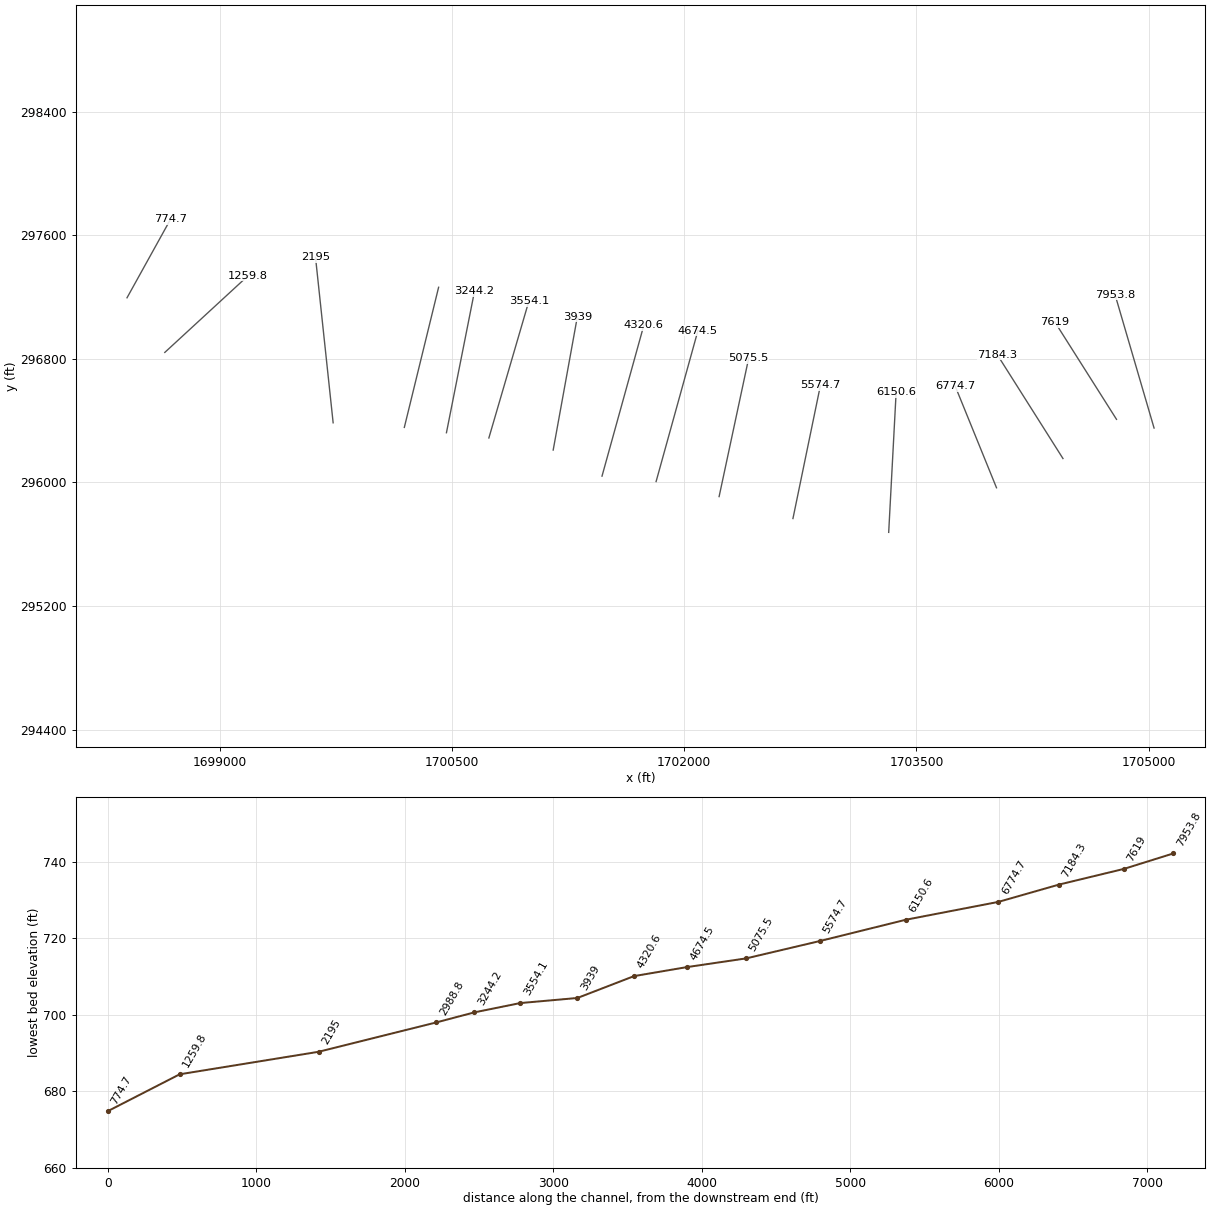
HEC-RAS study RUMCRK.prj: RUMCRK

--- RUMCRK.g01 (geometry) --- (continued)

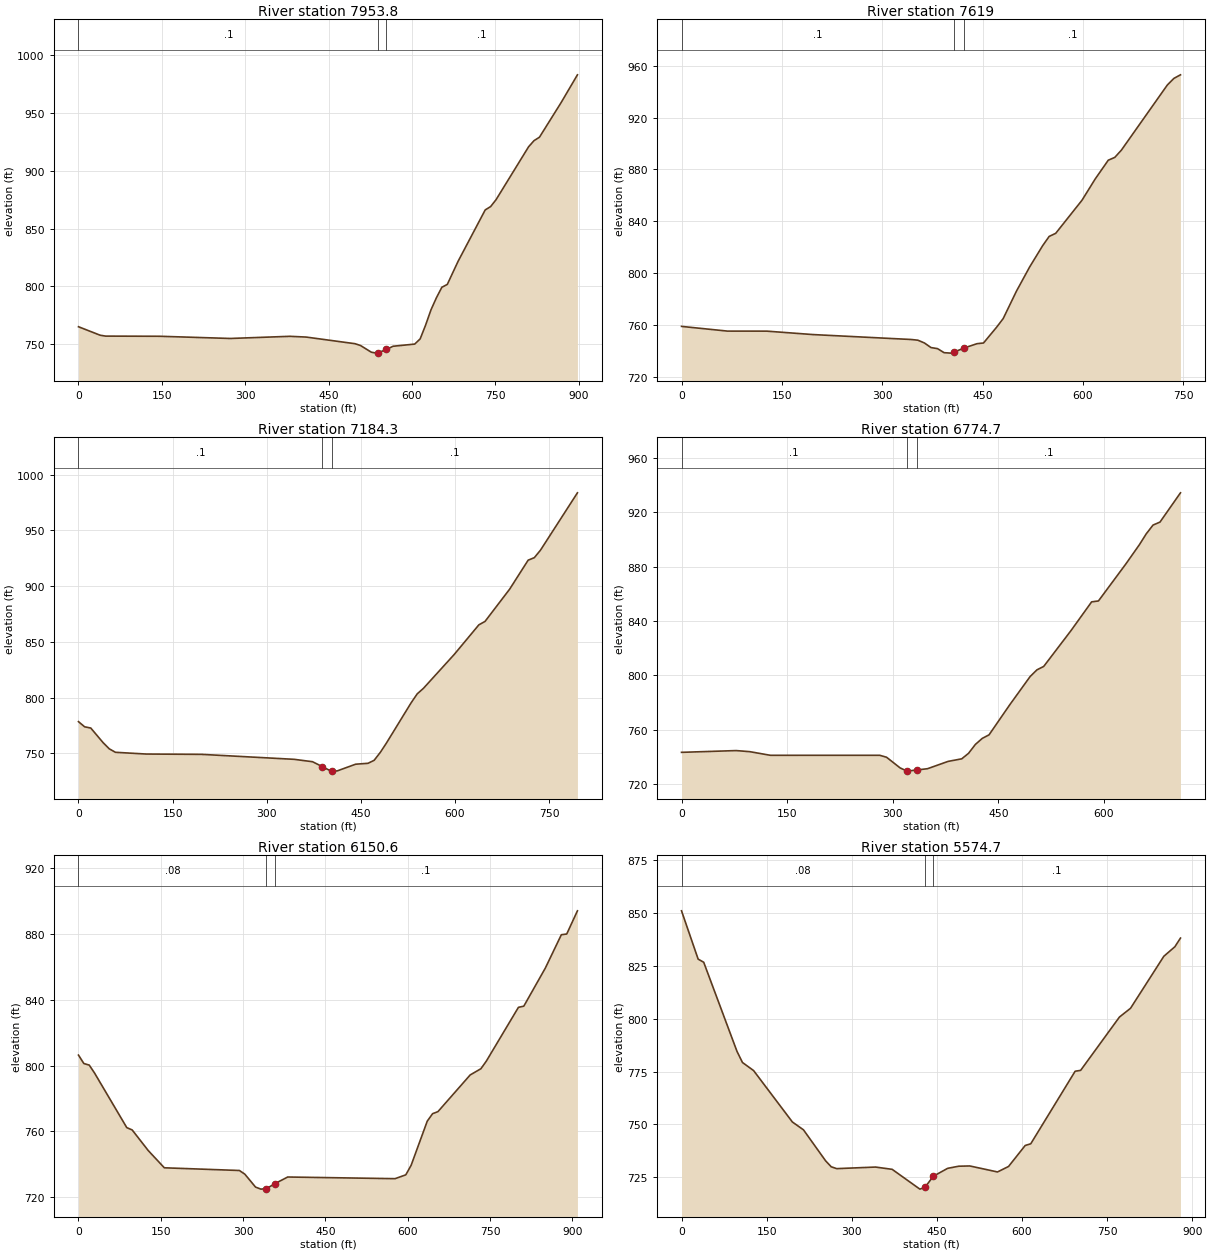
Type RM Length L Ch R = 1 ,7953.8  ,328.2,334.5,340.9
XS GIS Cut Line= 2
      1705034.35       296351.69      1704782.88      297213.212
#Sta/Elev= 30
       0  765.05      39  757.71    48.8  756.94   146.3   756.8   273.1   754.9
   380.4  756.76   409.7   756.1   497.5  750.36   507.3   748.8   526.8     743
   536.5  742.21     539  742.53     554  745.37   565.8  748.16   604.8  750.04
   614.6  754.53   624.3  766.36   634.1  779.72   643.8  790.09   653.6   799.2
   663.4  801.68   682.9  821.77   731.6  866.17   741.4  869.08   751.2   875.1
   809.7  920.86   819.4  926.12   829.2  929.13   868.2  959.13   897.5  983.11
#Mann= 3 , 0 , 0
       0      .1       0     539    .045       0     554      .1       0
Bank Sta=539,554
XS Rating Curve= 0 ,0
Exp/Cntr=0.3,0.1

Type RM Length L Ch R = 1 ,7619    ,435.2,434.9,434.6
XS GIS Cut Line= 2
     1704791.826       296408.03     1704393.498      297038.334
#Sta/Elev= 30
       0  758.79    68.7  755.16   127.5  755.13   196.2  752.49   343.4  748.67
   353.2  748.13     363  745.99   372.8  742.44   382.6  741.61   392.4  738.49
   402.2  738.15   407.5  738.99   422.5  742.13   441.5  745.43   451.3  745.98
   470.9   758.2   480.7  764.84   500.4  785.91     520  804.49   539.6  821.09
   549.4  828.29   559.2  830.69   598.5  856.27   618.1   872.6   637.7  887.15
   647.5  889.35   657.3  894.93     726  945.25   735.8  950.35   745.6   953.1
#Mann= 3 , 0 , 0
       0      .1       0   407.5    .045       0   422.5      .1       0
Bank Sta=407.5,422.5
XS Rating Curve= 0 ,0
Exp/Cntr=0.3,0.1

Type RM Length L Ch R = 1 ,7184.3  ,413.3,409.5,405.7
XS GIS Cut Line= 2
     1704446.087      296154.431     1704021.498      296826.897
#Sta/Elev= 30
       0  778.45     9.8  773.82    19.6  772.71    39.3  759.58    49.1  754.06
    58.9  750.96     108  749.39   196.4   749.1   343.6  744.66   373.1  742.51
   388.4  738.17   402.6  734.07   403.4  734.09   412.4  734.27   441.8  740.28
   461.5  741.09   471.3  743.78   481.1   750.9   490.9  759.29   530.2  795.34
     540  803.42   549.8   808.3   598.9  838.72   638.2  865.29     648  868.34
   687.3  897.32   716.7  923.26   726.6  925.54   736.4  932.26   795.3  983.69
#Mann= 3 , 0 , 0
       0      .1       0   388.4    .045       0   403.4      .1       0
Bank Sta=388.4,403.4
XS Rating Curve= 0 ,0
Exp/Cntr=0.3,0.1

Type RM Length L Ch R = 1 ,6774.7  ,633.9,623.9,613.9
XS GIS Cut Line= 2
     1704016.878      295965.272     1703750.499      296621.976
#Sta/Elev= 30
       0  743.35    77.7  744.64    97.1  743.83   126.2  741.17   281.5  741.18
   291.2  739.75   310.6  731.86   319.9  729.65   320.4  729.53   334.9  730.42
   349.5  731.32   378.6  736.68     398  738.58   407.7  742.63   417.4  749.17
   427.2  753.61   436.8  756.22     466  778.16   495.1  799.06   504.8     804
   514.5  806.56   553.4  833.02   582.5  854.03   592.2   854.7     631  881.82
   650.4   896.1   660.1  904.07   669.8  910.53   679.6   912.7   708.7  934.23
#Mann= 3 , 0 , 0
       0      .1       0   319.9    .045       0   334.9      .1       0
Bank Sta=319.9,334.9
XS Rating Curve= 0 ,0
Exp/Cntr=0.3,0.1

Type RM Length L Ch R = 1 ,6150.6  ,579.3,575.9,572.6
XS GIS Cut Line= 2
     1703320.669      295676.614     1703368.805       296584.39
#Sta/Elev= 30
       0  806.36     9.8  801.23    19.6  800.28    29.3  795.43      88  762.26
    97.8  760.85   127.1  748.31   156.4  737.83   293.2  736.19     303  733.97
   322.6  726.09   332.3  724.86   342.5  725.14   357.5  728.13   381.2  732.23
   576.7  731.22   596.3  733.55     606  739.34   635.4   766.2   645.1  770.73
   654.9  771.99   713.6  794.29   733.1  798.06   742.9  802.64   801.5   835.4
   811.3  836.12   850.4   859.2   879.7  879.56   889.5     880     909  894.09
#Mann= 3 , 0 , 0
       0     .08       0   342.5    .045       0   357.5      .1       0
Bank Sta=342.5,357.5
XS Rating Curve= 0 ,0
Exp/Cntr=0.3,0.1

Type RM Length L Ch R = 1 ,5574.7  ,499.1,498.8,498.6
XS GIS Cut Line= 2
     1702702.392      295766.193     1702879.728      296627.291
#Sta/Elev= 30
       0   851.1    29.3  828.23    39.1  826.75    97.7  784.59   107.4  779.28
     127  775.46   195.4   751.1   214.9   747.4     254  732.69   263.8   729.9
   273.5  729.02   341.9  729.77   371.2  728.69     420  719.32   428.8  720.14
   443.8  725.43   468.9  729.16   488.4  730.17     508  730.29   556.8  727.45
   576.3  730.06   605.6  739.99   615.4  740.79   693.6  775.14   703.3  775.56
   771.7  800.81   791.2  804.95   849.9  829.58   869.4  834.11   879.2  838.19
#Mann= 3 , 0 , 0
       0     .08       0   428.8    .045       0   443.8      .1       0
Bank Sta=428.8,443.8
XS Rating Curve= 0 ,0
Exp/Cntr=0.3,0.1

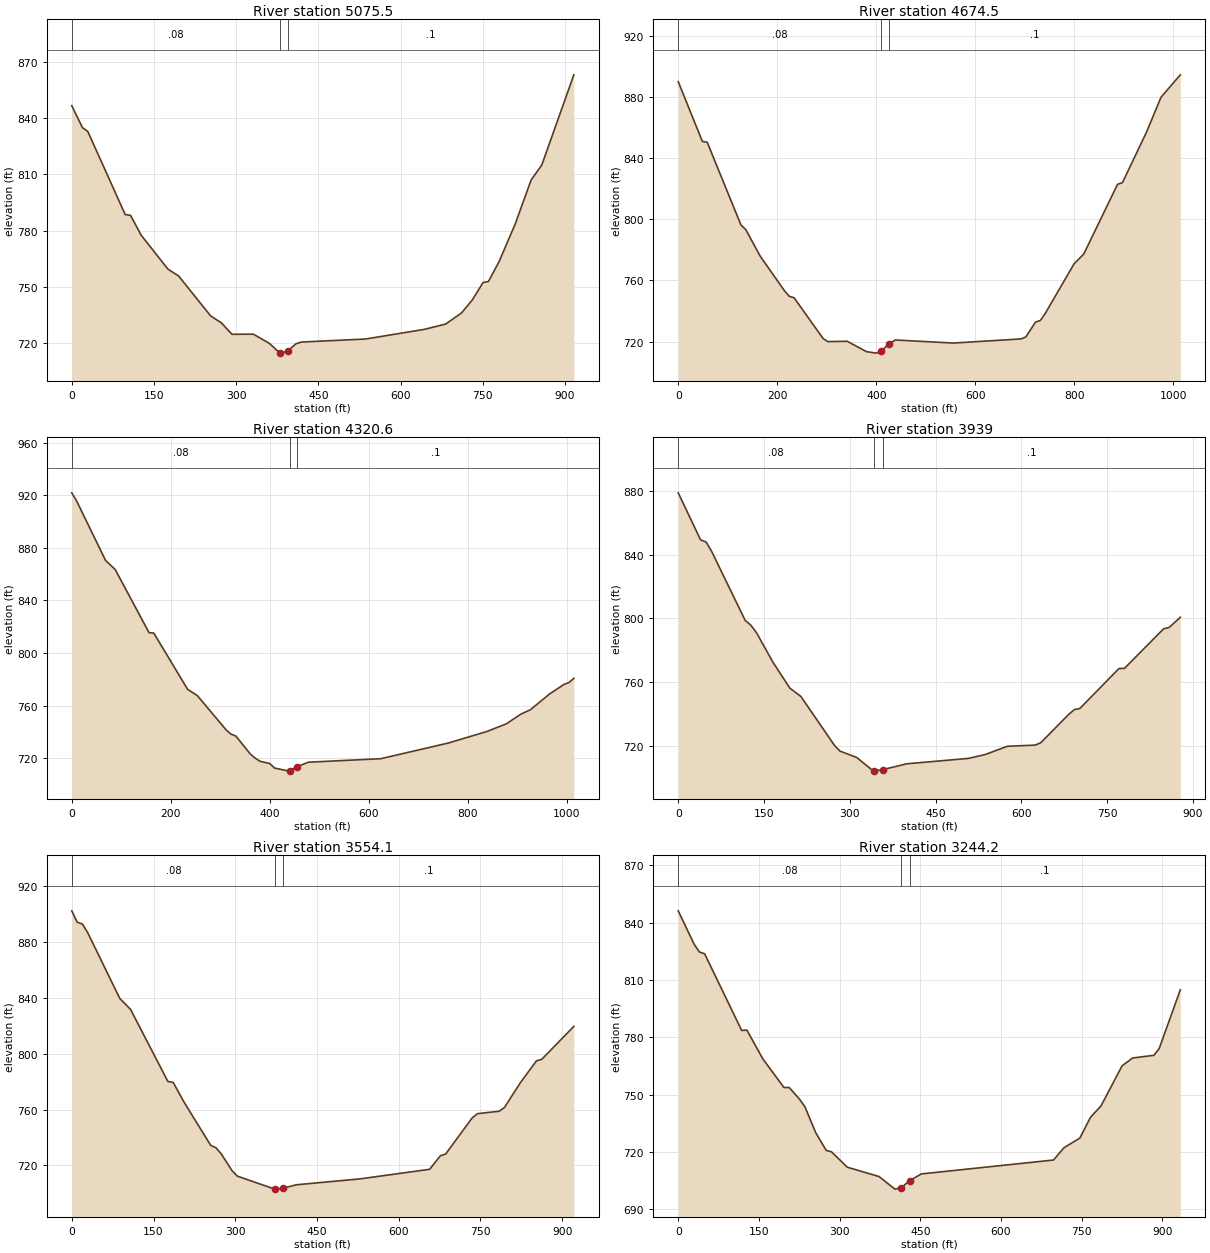
Type RM Length L Ch R = 1 ,5075.5  ,402.1,400.9,399.6
XS GIS Cut Line= 2
     1702225.515      295908.192     1702416.663      296804.134
#Sta/Elev= 30
       0   846.5    19.5  834.81    29.2  832.82    97.5  788.53   107.2  788.14
   126.7  777.54   175.4   759.5   194.9  755.85   253.4  734.58   272.9   730.9
   292.4  724.79   331.4  724.85   360.6  719.95   379.1  714.95   380.1  714.76
   394.1  715.89   409.3  719.78   419.1  720.66     536  722.27   643.2   727.4
   682.2  730.23   711.4  736.23   730.9   743.1   750.4  752.34   760.2  752.87
   779.7  763.47   808.9  783.36   838.1  806.89   857.6   814.9   916.1  862.93
#Mann= 3 , 0 , 0
       0     .08       0   379.1    .045       0   394.1      .1       0
Bank Sta=379.1,394.1
XS Rating Curve= 0 ,0
Exp/Cntr=0.3,0.1

Type RM Length L Ch R = 1 ,4674.5  ,353.9,353.9,354
XS GIS Cut Line= 2
     1701818.703      296005.611        1702089.      296982.769
#Sta/Elev= 30
       0  890.05    48.7  850.95    58.5   850.4   126.7  796.29   136.5   793.2
   165.7  775.79   214.5  753.27   224.2  749.64     234  748.66   292.5  722.02
   302.2  719.99   341.2  720.23   380.2  713.44   399.7  712.47     410  713.61
     425   718.6   438.7  721.06   555.7  719.06   692.2  721.76   701.9  723.04
   721.4  732.75   731.1   733.8   740.9  738.32   799.4  770.95   818.9  777.29
   887.1  822.92   896.9  823.94   945.6  857.06   974.9  879.88  1013.8   894.5
#Mann= 3 , 0 , 0
       0     .08       0     410    .045       0     425      .1       0
Bank Sta=410,425
XS Rating Curve= 0 ,0
Exp/Cntr=0.3,0.1

Type RM Length L Ch R = 1 ,4320.6  ,379.5,381.5,383.6
XS GIS Cut Line= 2
     1701469.373      296040.529     1701739.669      297017.687
#Sta/Elev= 30
       0  921.84     9.8  915.69    68.2  870.46    87.7  863.51     156  815.48
   165.7   815.1     234   772.3   253.5  767.61     312  741.37   321.7  738.23
   331.4  736.79   360.7  723.08   370.4  719.99   380.2  717.64   399.7  715.94
   409.4  712.48   438.7  710.13   440.6  710.47   455.6  713.63   477.7  716.91
   623.9  719.58   760.4  731.51   838.4  740.31   877.4   746.1   906.6  753.43
   926.1  756.84   965.1  768.93   994.4  776.21  1004.1  777.57  1013.8   780.7
#Mann= 3 , 0 , 0
       0     .08       0   440.6    .045       0   455.6      .1       0
Bank Sta=440.6,455.6
XS Rating Curve= 0 ,0
Exp/Cntr=0.3,0.1

Type RM Length L Ch R = 1 ,3939    ,387.1,384.8,382.4
XS GIS Cut Line= 2
     1701154.064      296209.317     1701310.364       297073.18
#Sta/Elev= 30
       0  878.66      39  849.24    48.8  847.83    58.5  841.95     117  798.81
   126.8  795.84   136.6  791.24   165.8  772.48   195.1   756.4   214.6  751.11
   273.1  720.56   282.9  716.94   312.1  712.95   341.4  704.41   342.2  704.41
   357.2  705.31   399.9  709.01   507.2  712.37   536.5  714.77   575.5  719.97
   624.3   720.7     634   722.2   682.8  739.97   692.6  742.92   702.3  743.65
   770.6  768.63   780.4  768.79   848.6   793.5   858.4  794.36   877.9  800.78
#Mann= 3 , 0 , 0
       0     .08       0   342.2    .045       0   357.2      .1       0
Bank Sta=342.2,357.2
XS Rating Curve= 0 ,0
Exp/Cntr=0.3,0.1

Type RM Length L Ch R = 1 ,3554.1  ,307.9,309.9,311.9
XS GIS Cut Line= 2
     1700738.728      296287.523     1700996.761      297172.058
#Sta/Elev= 30
       0  902.36     9.8  894.28    19.6  892.88    29.4   886.6    88.2  839.56
   107.8  831.83   176.4  780.18   186.2  779.43   205.8  765.55   254.9  734.48
   264.7  732.66   274.5  728.24   294.1  716.29   303.9  712.38   372.5  703.08
   373.3  703.09   388.3  703.73   411.7  706.16   529.3  710.43   656.8  717.28
   676.4  726.97   686.2  728.23   735.2  754.26     745  757.14   784.2  758.84
     794   761.5   823.4  779.34   852.8  794.96   862.6  796.05   921.4  819.63
#Mann= 3 , 0 , 0
       0     .08       0   373.3    .045       0   388.3      .1       0
Bank Sta=373.3,388.3
XS Rating Curve= 0 ,0
Exp/Cntr=0.3,0.1

Type RM Length L Ch R = 1 ,3244.2  ,256.4,255.4,254.5
XS GIS Cut Line= 2
     1700464.779       296321.47     1700646.049      297237.094
#Sta/Elev= 30
       0  846.27    29.5  828.84    39.3  824.76    49.1  823.78   117.9  783.69
   127.7  783.84   157.2  768.83   196.5  753.83   206.3  753.81     226  747.54
   235.8  743.58   255.5  730.23   275.1  720.92   284.9  720.15   314.4  712.11
   373.4  707.22   402.8  700.64     415  701.41     430  705.06     452   708.6
   697.6  715.86   717.2  722.32   746.7  727.37   766.4  738.22     786  744.19
   825.3  765.23     845  769.27   884.3  770.66   894.1  774.17   933.4  804.96
#Mann= 3 , 0 , 0
       0     .08       0     415    .045       0     430      .1       0
Bank Sta=415,430
XS Rating Curve= 0 ,0
Exp/Cntr=0.3,0.1

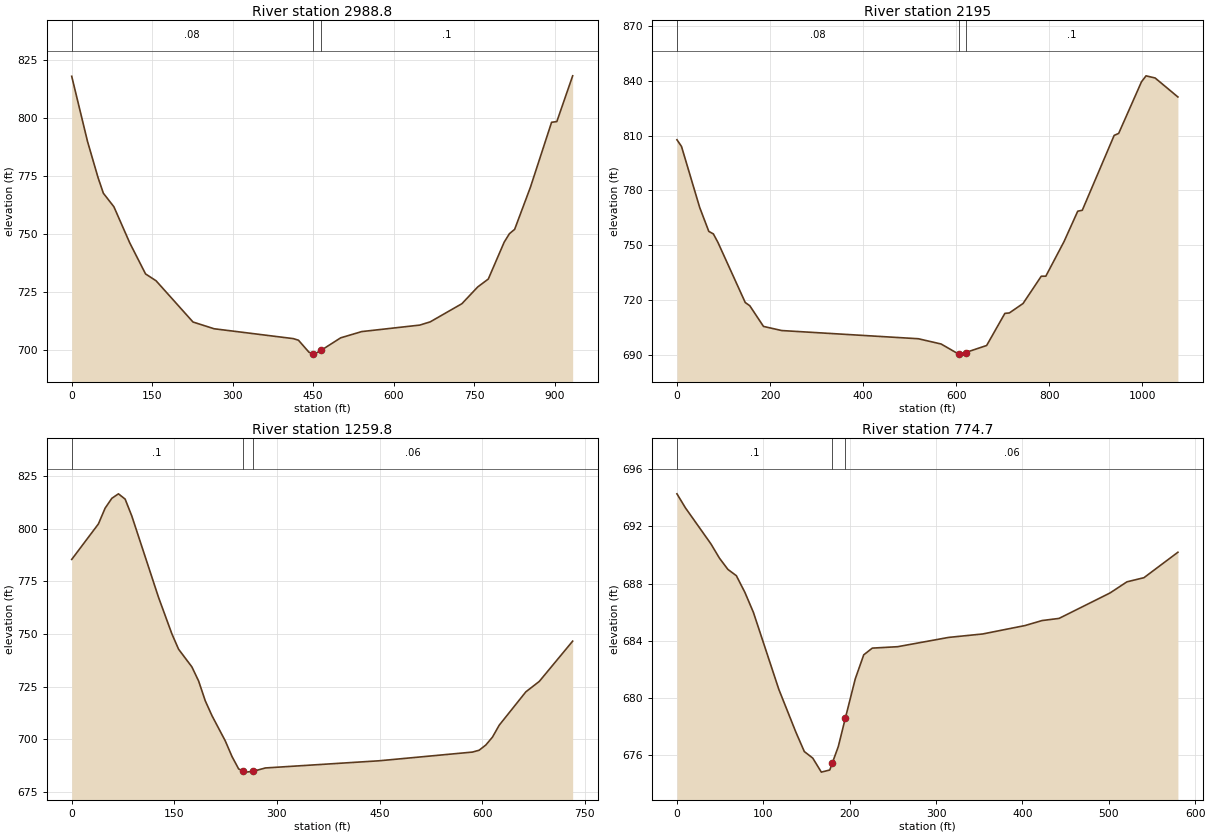
Type RM Length L Ch R = 1 ,2988.8  ,785.4,793.1,800.8
XS GIS Cut Line= 2
     1700192.824      296355.943     1700414.191      297262.709
#Sta/Elev= 30
       0  817.94    29.5  789.78    49.1   774.2      59  767.46    78.6  761.63
   108.1  746.06   137.6  732.63   157.2  729.68     226  711.88   265.3  708.97
   412.7  704.72   422.5  704.02   442.1  698.84   449.3  698.24     452  698.02
   464.3   699.6   501.1  705.05   540.4  707.75   648.5  710.55   668.1  711.96
   727.1   719.8   756.5  727.02   776.2  730.43   805.7   746.3   815.5  749.99
   825.3  751.88   854.8  770.13   894.1  798.08   903.9   798.4   933.4  818.14
#Mann= 3 , 0 , 0
       0     .08       0   449.3    .045       0   464.3      .1       0
Bank Sta=449.3,464.3
XS Rating Curve= 0 ,0
Exp/Cntr=0.3,0.1

Type RM Length L Ch R = 1 ,2195    ,955.9,935,914.1
XS GIS Cut Line= 2
     1699733.084      296385.653     1699619.261      297456.316
#Sta/Elev= 30
       0   807.7     9.8  804.02    48.9  770.61    68.5  757.52    78.3  756.15
    88.1   751.5   146.8  718.59   156.6  716.82     186  705.51   225.1  703.25
   518.8  698.76   567.7  695.89   605.2   690.4   606.9  690.34   620.2   691.2
   665.6  695.06   704.8  712.64   714.5  712.89   743.9  718.06     783  732.98
   792.8     733     832  751.97   861.4  768.58   871.2   769.1   939.7  810.08
   949.4  811.17   998.4   839.4  1008.2  842.69  1027.8   841.5  1076.7  831.11
#Mann= 3 , 0 , 0
       0     .08       0   605.2    .045       0   620.2      .1       0
Bank Sta=605.2,620.2
XS Rating Curve= 0 ,0
Exp/Cntr=0.3,0.1

Type RM Length L Ch R = 1 ,1259.8  ,477.9,485.2,492.5
XS GIS Cut Line= 2
     1698646.019      296841.114     1699184.091      297337.641
#Sta/Elev= 30
       0  785.47      39  802.32    48.8   809.8    58.6  814.48    68.3  816.63
    78.1  814.12    87.9  806.04   126.9  767.46   146.4  750.14   156.2  742.84
   175.7  734.41   185.5  727.72   195.2  718.34     205  711.28   224.5  699.26
   234.3  691.86     244  685.98   249.8  685.08   253.8  684.46   264.8  684.81
   283.1  686.44   449.1  689.84   585.7  693.98   595.5  694.86   605.2  697.32
     615  701.09   624.8  706.73   663.8   722.6   683.4  727.54   732.2  746.67
#Mann= 3 , 0 , 0
       0      .1       0   249.8    .045       0   264.8     .06       0
Bank Sta=249.8,264.8
XS Rating Curve= 0 ,0
Exp/Cntr=0.3,0.1

Type RM Length L Ch R = 1 ,774.7   ,763.6,774.4,785.2
XS GIS Cut Line= 2
     1698402.021      297194.688     1698682.805      297702.339
#Sta/Elev= 30
       0  694.28     9.8   693.3    39.3  690.78    49.2  689.78      59  688.99
    68.8  688.55    78.7  687.38    88.5  685.99     118  680.59   137.7   677.6
   147.5  676.24   157.3  675.78   167.2   674.8     177  674.95   180.1  675.47
   186.8  676.58   195.1   678.6   206.5  681.33   216.3  683.01   226.2  683.48
   255.6  683.58   314.6  684.23     354  684.47   403.1  685.06   422.8  685.41
   442.5  685.56   501.5  687.34   521.1  688.12   540.8  688.41   580.1  690.19
#Mann= 3 , 0 , 0
       0      .1       0   180.1    .045       0   195.1     .06       0
Bank Sta=180.1,195.1
XS Rating Curve= 0 ,0
Exp/Cntr=0.3,0.1

Chan Stop Cuts=-1
Use User Specified Reach Order=0
Composite Channel Slope=5